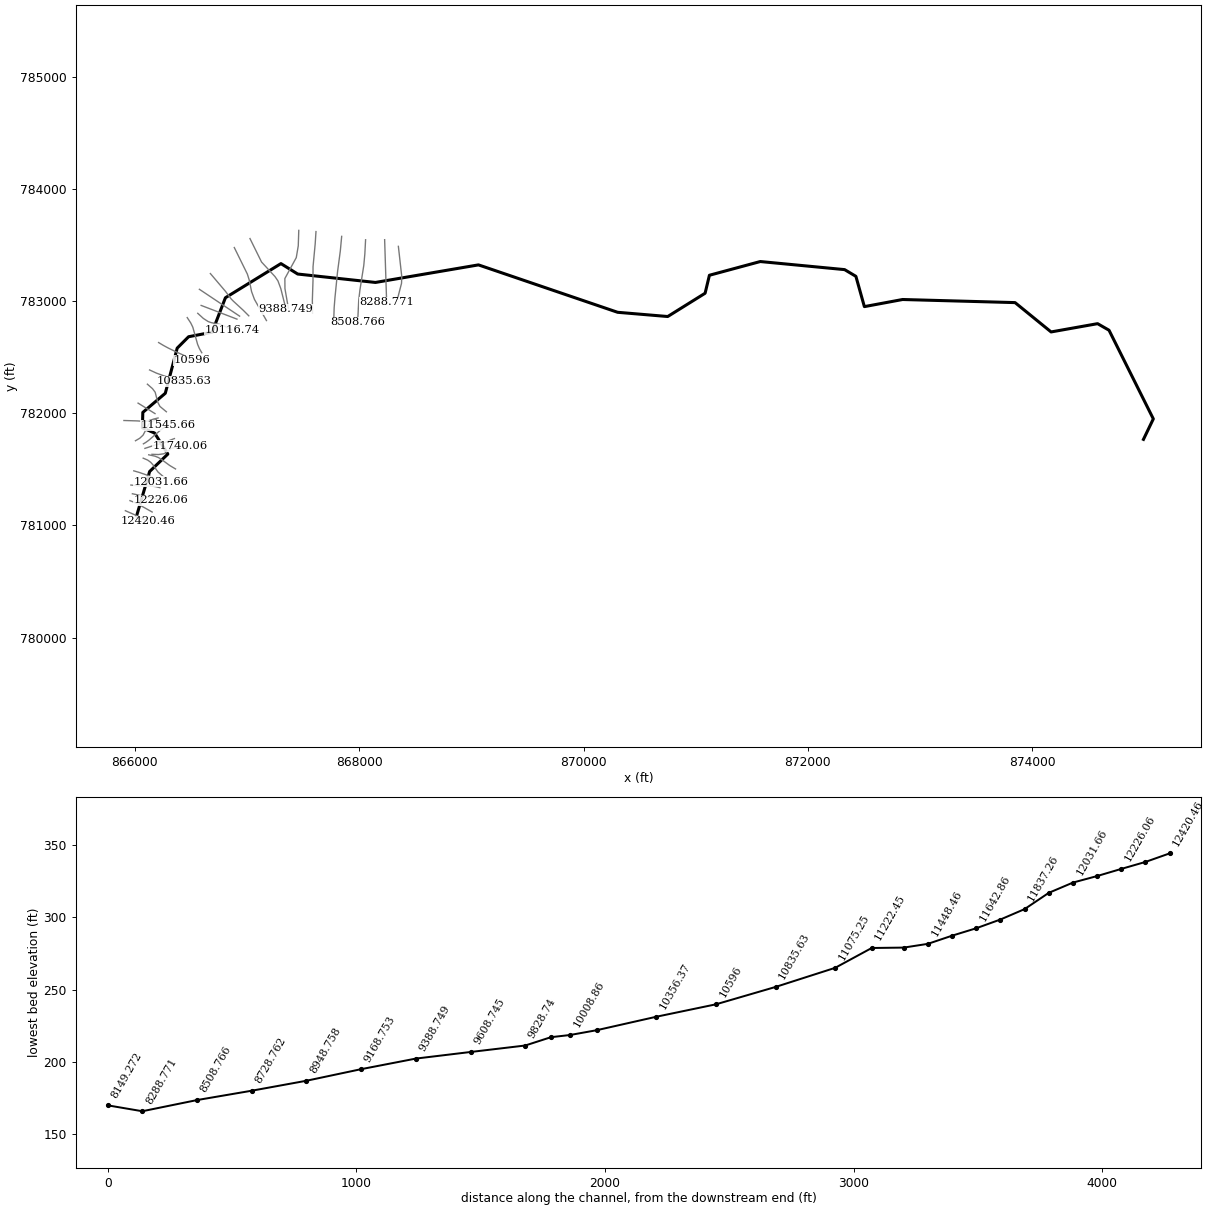
--- 11666_ras.prj (project) ---

Proj Title=11666
Current Plan=p01
Default Exp/Contr=0.3,0.1
English Units
Geom File=g01
Flow File=f01
Plan File=p01
Y Axis Title=Elevation
X Axis Title(PF)=Main Channel Distance
X Axis Title(XS)=Station
BEGIN DESCRIPTION:
RFD model 11666 exported to HEC-RAS
END DESCRIPTION:

--- 11666_ras.p01 (plan) ---

Plan Title=Plan 01
Program Version=4.10
Short Identifier=Plan 01
Geom File=g01
Flow File=f01
Subcritical Flow
Calc Critical at every XS
Secant Critical Depth

--- 11666_ras.f01 (steady flow) ---

Flow Title=Flow 01
Program Version=5.01
Number of Profiles= 6
Profile Names=10yr,25yr,50yr,100yr,100plus,500yr
River Rch & RM=11666,49,12420.46
  266.28  397.84  513.75  609.64  890.07 1350.98
River Rch & RM=11666,49,12323.26
  269.29  402.37  519.64  616.65   900.3 1364.43
River Rch & RM=11666,49,12226.06
   321.7  481.75  623.17   740.4 1080.99 1600.47
River Rch & RM=11666,49,12128.86
  324.08  485.35  627.86     746 1089.15 1610.96
River Rch & RM=11666,49,12031.66
  326.47  488.96  632.55   751.6 1097.33 1621.42
River Rch & RM=11666,49,11837.26
  342.93  513.88  665.03   790.4 1153.98 1693.95
River Rch & RM=11666,49,11740.06
  345.32  517.47   669.7  795.95 1162.09 1704.21
River Rch & RM=11666,49,11642.86
  349.17  523.25   677.2  804.87 1175.11 1720.57
River Rch & RM=11666,49,11351.25
  396.89  594.61  769.51  914.36 1334.96 1918.36
River Rch & RM=11666,49,11075.25
  399.23  598.13  774.08  919.78 1342.88 1928.13
River Rch & RM=11666,49,10835.63
  423.49  634.71  821.68  976.52 1425.72 2030.56
River Rch & RM=11666,49,   10596
  441.01  661.02   855.8  1017.1 1484.96 2102.77
River Rch & RM=11666,49,10356.37
  446.88  669.87  867.32 1030.82 1504.99 2127.25
River Rch & RM=11666,49,10116.74
  455.42  682.76  884.09  1050.8 1534.17 2162.82
River Rch & RM=11666,49,10008.86
  456.77  684.79  886.73 1053.95 1538.77 2168.42
River Rch & RM=11666,49,9932.198
  457.69  686.16  888.51 1056.07 1541.86 2172.15
River Rch & RM=11666,49, 9828.74
  742.47 1099.21 1412.32 1665.44 2431.55  3153.9
River Rch & RM=11666,49,9608.745
 1093.23 1631.42 2107.76 2496.65  3645.1 4508.02
River Rch & RM=11666,49,9388.749
 1101.84 1644.46  2124.8 2516.98  3674.8 4540.14
River Rch & RM=11666,49,9168.753
 1112.03 1659.86 2144.86  2540.9 3709.72 4577.74
River Rch & RM=11666,49,8948.758
 1116.53 1666.66 2153.74  2551.5 3725.19 4594.42
River Rch & RM=11666,49,8728.762
 1122.31  1675.5 2165.34 2565.42 3745.51 4616.61
River Rch & RM=11666,49,8508.766
 1137.74  1699.1 2196.35 2602.66 3799.89 4676.05
River Rch & RM=11666,49,8288.771
 1165.83 1741.99 2252.64 2670.17 3898.44 4783.11
River Rch & RM=11666,49,8149.272
  1170.8  1749.6 2262.64 2682.19 3915.99 4802.23
River Rch & RM=11666,49,8024.771
 1178.26 1761.02 2277.65 2700.22 3942.32 4830.85
River Rch & RM=11666,49,7763.599
 1215.33  1817.8 2352.32 2789.94 4073.31 4972.97
River Rch & RM=11666,49, 7609.55
 1220.25 1825.35 2362.24 2801.85 4090.71  4991.8
River Rch & RM=11666,49,7445.487
 1221.26 1826.91 2364.31 2804.36 4094.37 4995.83
River Rch & RM=11666,49, 7343.31
 1236.69 1850.55  2395.4 2841.73 4148.92  5054.8
River Rch & RM=11666,49,7121.487
 1264.66 1893.69 2452.39 2910.47 4249.28    5164
River Rch & RM=11666,49,6883.297
 1287.11 1928.29 2498.08 2965.57 4329.74 5251.23
River Rch & RM=11666,49,6645.108
 1301.14 1950.17 2527.16 3000.86 4381.25 5307.76
River Rch & RM=11666,49,6406.918
 1306.04  1957.8  2537.3 3013.15  4399.2 5327.42
River Rch & RM=11666,49,6168.729
 1309.29 1962.87 2544.04 3021.33 4411.14 5340.52
River Rch & RM=11666,49,5930.539
 1318.41 1977.08 2562.93 3044.24 4444.59 5377.11
River Rch & RM=11666,49, 5692.35
 1382.62 2076.18  2693.9  3202.3 4675.35 5625.48
River Rch & RM=11666,49,5533.811
 1385.06 2080.04 2699.08 3208.63 4684.61 5635.73
River Rch & RM=11666,49,5387.823
 1387.78 2084.36 2704.88 3215.74 4694.98 5647.26
River Rch & RM=11666,49,5061.572
 1395.38 2096.39 2721.04 3235.51 4723.85 5679.23
Boundary for River Rch & Prof#=11666,49,1
Up Type= 0
Dn Type= 2
Boundary for River Rch & Prof#=11666,49,2
Up Type= 0
Dn Type= 2
Boundary for River Rch & Prof#=11666,49,2
Up Type= 0
Dn Type= 2
Boundary for River Rch & Prof#=11666,49,2
Up Type= 0
Dn Type= 2
Boundary for River Rch & Prof#=11666,49,2
Up Type= 0
Dn Type= 2
Boundary for River Rch & Prof#=11666,49,2
Up Type= 0
Dn Type= 2

--- 11666_ras.g01 (geometry) ---

Geom Title=11666
Program Version=4.10

River Reach=11666,49
Reach XY= 30
866015.766372172781085.506346758866131.856614067781480.911333352
866294.217256947 781636.40347881866176.127447399781823.793277801
866067.620502956781870.668277801866071.092725177782007.821055582
866271.511717967782178.388690049866377.516336285782580.737722251
866479.078836286782682.300222233866688.708862391782722.642830274
866807.515219582783030.020364077 867302.37095493783334.305208291
867451.780140238783241.237065582868144.753188425783166.282953505
869063.113860112783322.854800954870303.731614067782900.182166691
870750.303692909782862.529868319 871083.50271462 783070.11004369
871121.923791318783230.325525158871575.313645305783352.681443311
872327.049756439783280.632832206872427.744200857783220.736998872
872503.265034231782950.771721091872844.044267833783014.214113674
 873846.58100647782986.579012732874167.761561991782725.077276642
874582.258089783782798.861998871874684.254617572782740.268248875
875079.009183765781950.000781693874991.177874179781767.317605594

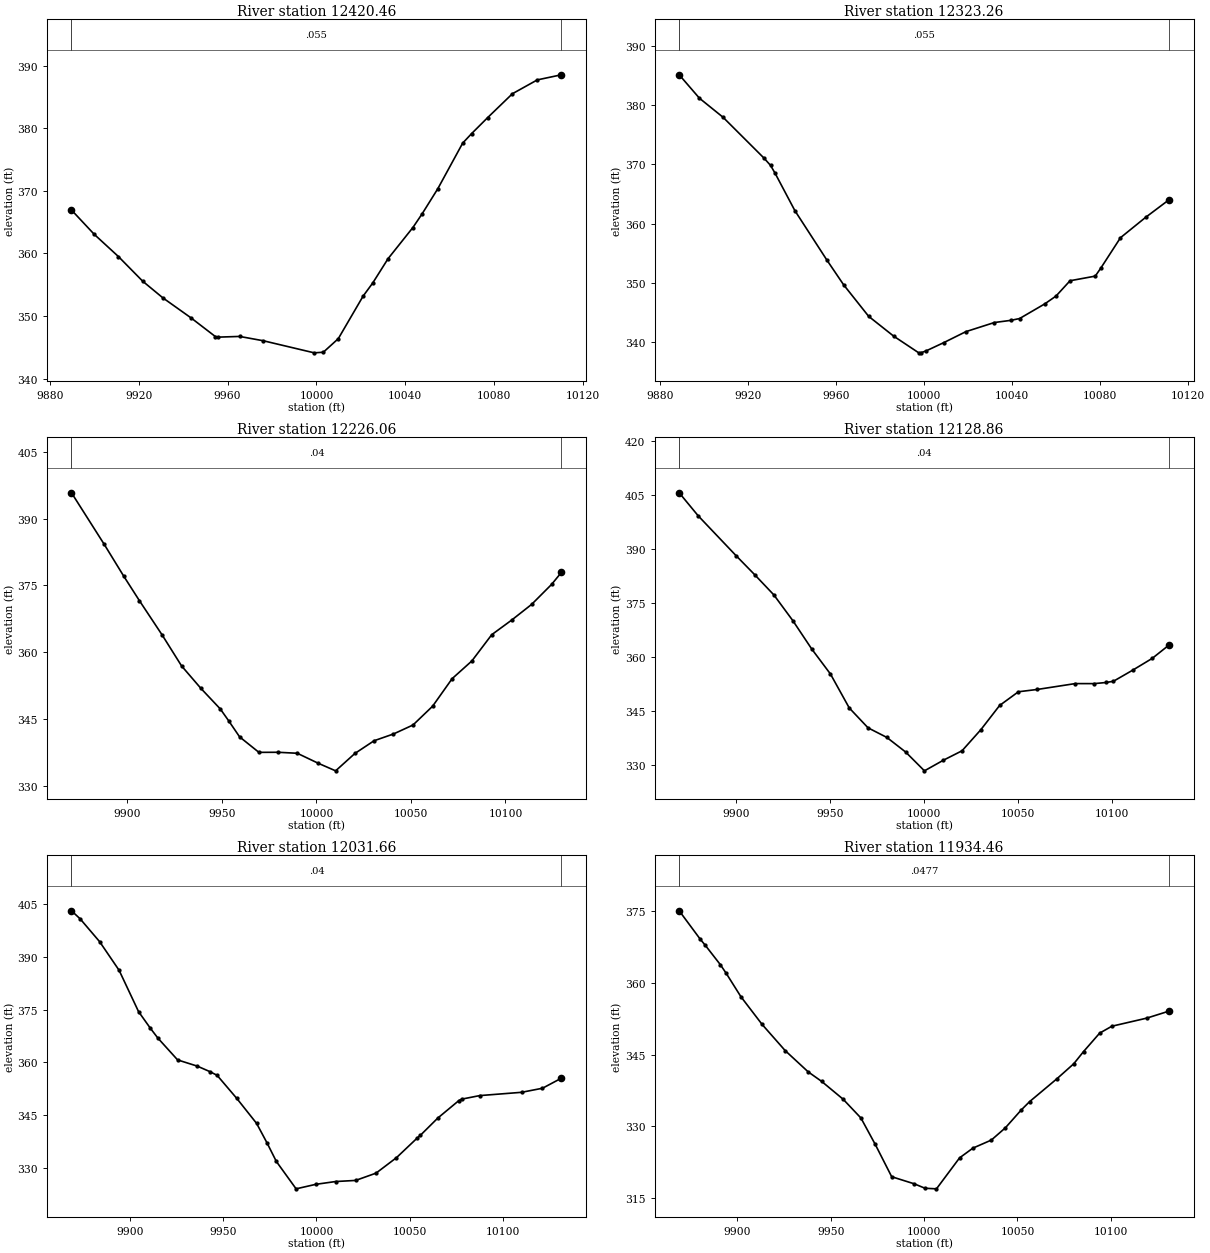
Type RM Length L Ch R = 1 ,12420.46,97.200500,97.200500,97.200500
XS GIS Cut Line= 5
865915.600434821781131.387082441865994.797921492781096.941385789
866015.327650446 781086.85078837866017.110813784781085.945068483
866114.687572866781036.805260333
#Sta/Elev= 25
 9889.76366.94359900.011363.05649910.915 359.495 9921.82355.56199930.847352.9133
 9943.63349.68429954.535346.70959955.919346.6244 9965.44346.73469976.124346.0416
    9999344.1122 10003.1344.209310009.83346.372610021.03 353.19110025.33355.2727
10032.23359.160810043.42364.146910047.57366.333910054.62 370.34510065.82377.6368
 10069.8379.146710077.01381.697410088.21385.534610099.41387.746410110.25388.5632
#Mann= 3 , 0 , 0
 9889.76   0.055       0 9889.76   0.055       010110.25   0.055       0
#XS Ineff= 2 , 0
       0                               0
Bank Sta=9889.76,10110.25
Exp/Cntr=0.3,0.1

Type RM Length L Ch R = 1 ,12323.26,97.200500,97.200500,97.200500
XS GIS Cut Line= 6
865956.428545051781221.234611268865992.273100098781207.169629684
866023.892445876781192.288072636866056.293029089781174.755574991
 866058.03307346781173.769549847866154.275789193781119.902167418
#Sta/Elev= 27
9888.708385.12579897.916381.16839908.658377.94939927.214371.07479930.228369.8281
9932.309  368.49 9941.28362.19519955.792 353.8729963.419349.68959974.789344.3688
 9986.16341.0244 9997.53338.21669998.486338.2102   10001338.557110008.98339.9444
10018.96341.7859 10031.9343.325810039.43343.693610043.36343.996810054.82346.4748
 10059.9347.788510066.28350.373410077.74351.156210080.38352.5751 10089.2357.6354
10100.66361.081710111.29364.0487
#Mann= 3 , 0 , 0
9888.708   0.055       09888.708   0.055       010111.29   0.055       0
#XS Ineff= 2 , 0
       0                               0
Bank Sta=9888.708,10111.29
Exp/Cntr=0.3,0.1

Type RM Length L Ch R = 1 ,12226.06,97.200500,97.200500,97.200500
XS GIS Cut Line= 6
865978.068248522781282.619546237866074.011736989781261.805012172
866106.015844665781256.513036082866141.796671636781249.754078513
866181.660397862781239.048669388866229.943180108781222.922390838
#Sta/Elev= 27
9870.385395.8041 9887.71384.22949897.943377.15149906.324371.59259918.408363.8558
9928.641356.93699938.873351.89489949.106347.2914 9953.49344.66619959.339341.0178
9969.562337.54239979.702337.56039989.841337.3387   10001335.083610010.14333.3944
10020.32337.2913 10030.5340.152310040.73341.664110051.08343.682410061.44347.8941
10071.79354.089310082.21358.054810092.75363.9579 10103.3367.236510113.84370.7536
10124.38375.229310129.59377.9269
#Mann= 3 , 0 , 0
9870.385    0.04       09870.385    0.04       010129.59    0.04       0
#XS Ineff= 2 , 0
       0                               0
Bank Sta=9870.385,10129.59
Exp/Cntr=0.3,0.1

Type RM Length L Ch R = 1 ,12128.86,97.200400,97.200400,97.200400
XS GIS Cut Line= 6
865964.908679182781360.314075159866035.817332921781352.541417181
866095.852167105781351.480166585866155.101012882781350.653823239
866189.759489527781345.386259954 866223.67171668781336.520266703
#Sta/Elev= 26
9869.611405.62569879.762399.21259899.882388.17759909.942382.81269920.002377.2816
9930.062370.16639940.122362.29669950.128355.32549960.129 345.911 9970.13340.3929
9980.131337.73349990.132333.681810000.14328.459510010.15331.387110020.15334.0253
10030.15339.867510040.15346.598610050.15350.403710060.25351.048910080.38352.6706
 10090.5352.663910096.84352.979210100.73353.318510111.06356.4214 10121.4359.6788
10130.36363.3928
#Mann= 3 , 0 , 0
9869.611    0.04       09869.611    0.04       010130.36    0.04       0
#XS Ineff= 2 , 0
       0                               0
Bank Sta=9869.611,10130.36
Exp/Cntr=0.3,0.1

Type RM Length L Ch R = 1 ,12031.66,97.200500,97.200500,97.200500
XS GIS Cut Line= 6
865990.518844924781486.927341718866040.414592053781472.263813169
866116.277482613781446.146585632866131.001570597781440.935032734
866165.992527484781425.346691038866234.031151529781390.784050073
#Sta/Elev= 30
9868.758403.17439873.429400.86229883.852394.36289894.275 386.2199904.698374.4412
 9911.06369.6765 9915.12366.85589925.616360.68519936.197358.90529942.986357.3293
9946.778356.2953 9957.36349.69089967.941342.59649973.579  336.989978.522331.7495
9989.104323.94939999.672325.235710010.25326.0299   10021 326.34610031.94328.4242
10042.89332.835210053.84338.350510055.69339.201710065.03344.122410076.24349.0686
10077.77349.500610087.46350.515810109.89 351.45110121.11352.611710131.24355.4799
#Mann= 3 , 0 , 0
9868.758    0.04       09868.758    0.04       010131.24    0.04       0
#XS Ineff= 2 , 0
       0                               0
Bank Sta=9868.758,10131.24
Exp/Cntr=0.3,0.1

Type RM Length L Ch R = 1 ,11934.46,97.200500,97.200500,97.200500
XS GIS Cut Line= 6
866074.390508611781599.889559612866114.186025897781582.838862718
866140.773678237781563.510098233866160.174710696781542.309394628
866206.798630072781476.112043048866264.560981531781426.472736749
#Sta/Elev= 30
9868.876375.1297  9880.2369.14689882.865367.89089890.873363.85819894.002362.0549
9901.933357.11659913.245351.32659925.608345.83429937.972341.3628 9945.11339.3873
9956.645335.64359966.183331.70149973.848 326.1729982.655319.39539994.704317.9127
10000.51316.978510006.63316.857610019.01323.352910026.16325.395710035.99 327.074
10043.53 329.64810052.02333.3871 10056.5335.134610070.94339.865110080.14343.0703
10085.37345.620110094.01349.491110100.54 350.93710119.19352.630610131.19354.1095
#Mann= 3 , 0 , 0
9868.876  0.0477       09868.876  0.0477       010131.19  0.0477       0
#XS Ineff= 2 , 0
       0                               0
Bank Sta=9868.876,10131.19
Exp/Cntr=0.3,0.1

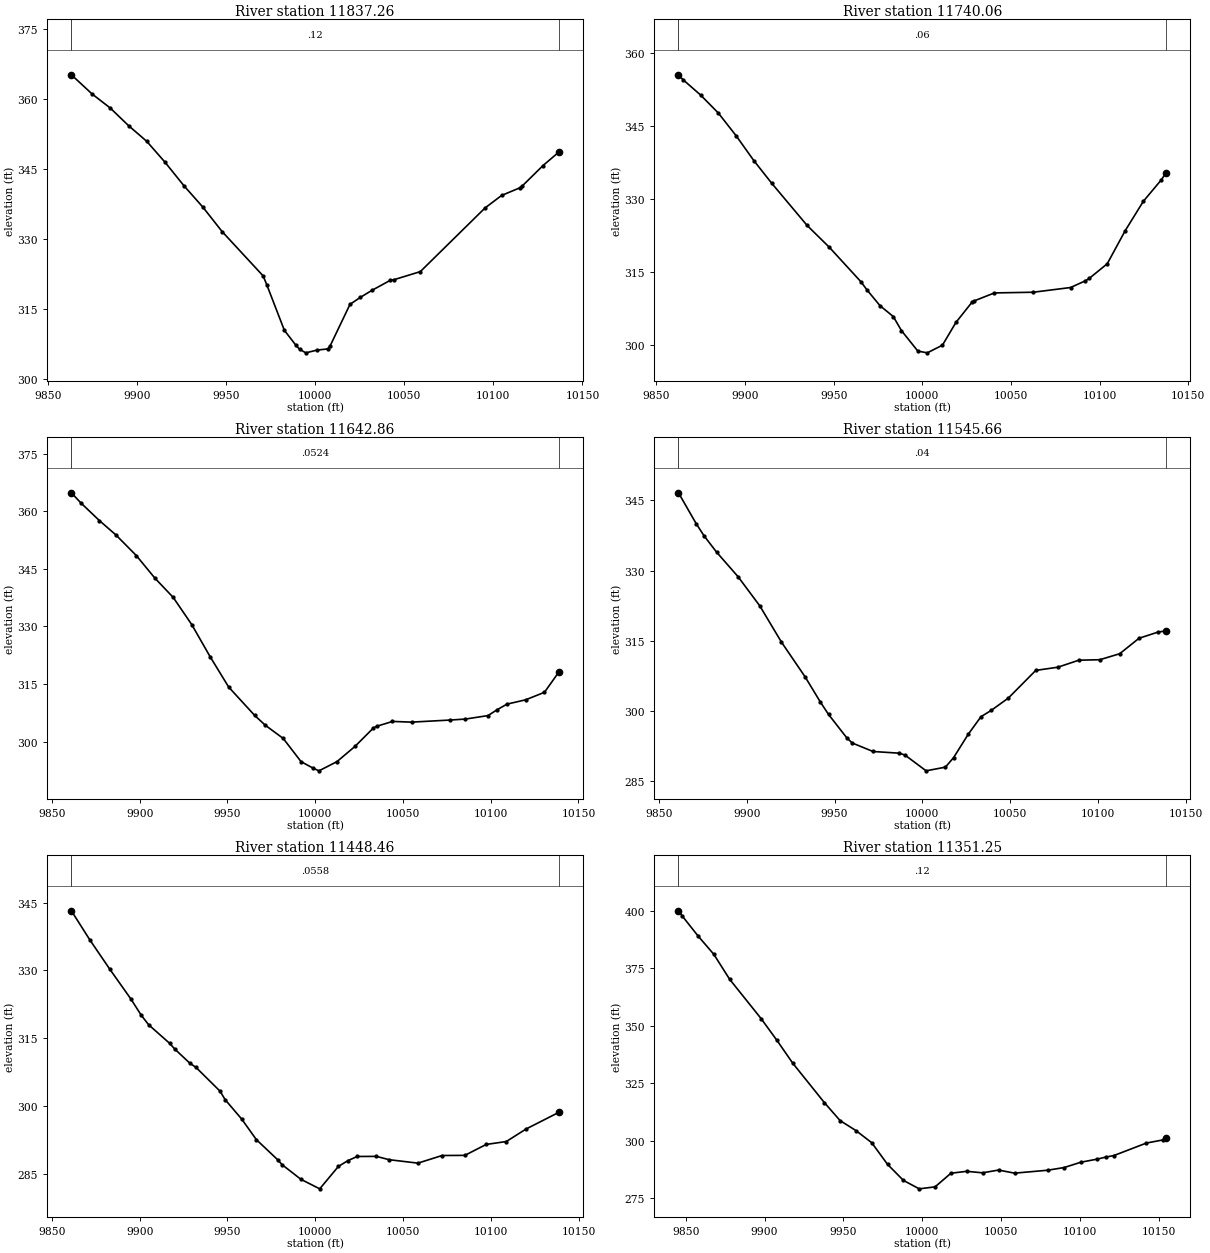
Type RM Length L Ch R = 1 ,11837.26,97.200500,97.200500,97.200500
XS GIS Cut Line= 6
866123.678803255781629.849334233866179.225775578781617.645953569
866211.162651235781605.026517289866240.501219738781586.215857944
866310.762821564 781534.69162633866362.643098039781503.736677591
#Sta/Elev= 30
9863.236365.28269874.827361.17829885.066358.14759895.304354.37999905.543351.0047
9915.781346.52679926.316341.52049937.069336.87129947.821331.64899970.885322.1171
9973.024320.10269982.763310.45839989.298 307.226  9991.4306.36159994.813305.6271
   10001306.209510007.16306.472810008.49307.154610019.58316.023610025.34317.5145
   10032319.0545 10042.2321.185410044.43321.337310059.05323.052310095.34336.6978
10104.65339.390310114.86341.0211 10116.3341.448710127.94345.818810136.84348.7183
#Mann= 3 , 0 , 0
9863.236    0.12       09863.236    0.12       010136.84    0.12       0
#XS Ineff= 2 , 0
       0                               0
Bank Sta=9863.236,10136.84
Exp/Cntr=0.3,0.1

Type RM Length L Ch R = 1 ,11740.06,97.200500,97.200500,97.200500
XS GIS Cut Line= 6
866152.553544777781634.197830116866210.483395761781632.249650591
866258.160085143781638.954696321866271.689605667 781644.82973319
866322.247841539781685.876490038866407.604291788781707.856376538
#Sta/Elev= 30
9862.484355.47619864.935354.50689874.956351.32739884.977347.62829894.997342.9796
9905.001337.87139915.002333.26139935.066 324.567 9947.56320.10289965.469312.9986
9968.686311.41079976.143308.12279983.671305.88339988.233303.01729997.488298.8085
10002.84298.446310011.38300.021510019.01304.697910027.95308.787910029.03309.0655
10040.69 310.73610062.58310.876610083.68311.8455   10092313.224110094.15313.7037
10104.32316.7163 10114.5323.532510124.67329.514310134.84333.934210137.49335.3875
#Mann= 3 , 0 , 0
9862.484    0.06       09862.484    0.06       010137.49    0.06       0
#XS Ineff= 2 , 0
       0                               0
Bank Sta=9862.484,10137.49
Exp/Cntr=0.3,0.1

Type RM Length L Ch R = 1 ,11642.86,97.200500,97.200500,97.200500
XS GIS Cut Line= 6
866089.860677069781687.037711691866189.052075106781719.737324972
866223.862417363781726.455707633866250.822146444781732.501181217
866319.545465879781762.046515876866352.714976824781774.561441081
#Sta/Elev= 30
9861.101364.81999866.512362.18169877.041357.59789886.532353.8192  9898.1 348.477
9908.629342.62639919.159 337.5529929.688330.49719940.218322.08619950.747314.2132
9965.543306.84029971.605304.28049981.797300.84689991.989294.7958    9999293.0676
10002.17292.408910012.41294.804310022.66298.761110033.18303.566810034.96303.9929
10044.06305.272810054.95305.095110076.72305.633710085.59305.890310098.49306.8018
10103.43308.253610109.26309.778910119.95310.908610130.64312.861310138.89318.1739
#Mann= 3 , 0 , 0
9861.101  0.0524       09861.101  0.0524       010138.89  0.0524       0
#XS Ineff= 2 , 0
       0                               0
Bank Sta=9861.101,10138.89
Exp/Cntr=0.3,0.1

Type RM Length L Ch R = 1 ,11545.66,97.200500,97.200500,97.200500
XS GIS Cut Line= 6
866076.252616868781727.615313232 866096.90406983781739.743406727
866125.233073067781760.333450048866235.683253597781855.945536509
866269.026114248 781877.58792426866298.936868992 781891.53189142
#Sta/Elev= 30
 9861.07346.62279871.214340.00689875.652 337.4399882.811333.94299895.028328.7135
 9907.39322.49499919.752314.74999933.167 307.3769941.993301.92399946.606299.2997
9956.961 294.3289960.046293.22069971.929291.40159986.925291.0397 9990.18290.6303
10002.19287.272110013.19288.061210017.81290.075710026.21295.094810033.43298.8215
10039.22300.157810049.05302.807610064.67308.709810077.26309.391810089.18310.8871
10101.15310.990610112.49312.267810123.52315.573710134.56316.9125 10138.9317.1299
#Mann= 3 , 0 , 0
 9861.07    0.04       0 9861.07    0.04       0 10138.9    0.04       0
#XS Ineff= 2 , 0
       0                               0
Bank Sta=9861.07,10138.9
Exp/Cntr=0.3,0.1

Type RM Length L Ch R = 1 ,11448.46,97.200500,97.200500,97.200500
XS GIS Cut Line= 6
866005.585764438781755.175925678866043.622359771781777.293176312
866073.388769112781805.183033724866126.102436847781905.497536852
 866154.16315404781928.263934931866192.269901264781946.680591795
#Sta/Elev= 30
9861.106343.19289871.723336.6923    9883330.2639 9894.83323.76849901.003320.0226
9905.163317.9457 9917.14313.83499920.028312.57339928.498309.48559932.163308.4992
9945.784303.2633 9948.78301.34459958.153297.07689966.488292.5327 9978.58288.0964
9981.157286.98069991.871283.744410002.59281.636110013.25 286.60710018.61287.8701
10023.91288.796910034.87288.823610042.16288.084510058.53 287.327 10072.3289.0162
10085.25289.044910097.43291.465710108.88292.109910120.14294.883110138.86298.5815
#Mann= 3 , 0 , 0
9861.106  0.0558       09861.106  0.0558       010138.86  0.0558       0
#XS Ineff= 2 , 0
       0                               0
Bank Sta=9861.106,10138.86
Exp/Cntr=0.3,0.1

Type RM Length L Ch R = 1 ,11351.25,128.800200,128.800200,128.800200
XS GIS Cut Line= 6
 865902.58306443781935.651252881866018.482046866781932.129704847
866091.340838335781927.344754098866116.762474534781931.772382129
866170.319230834781949.079567561 866207.14530107781958.141103438
#Sta/Elev= 30
9845.447399.89419847.865397.6137 9857.87388.93999867.874380.96439877.879370.1341
9897.888 352.9789907.893343.54639917.897333.64119937.907 316.5369947.911 308.695
9957.916304.38069967.939299.08719977.973289.68199988.006282.7257 9998.04279.0434
 10008.1279.899810018.13285.822310028.13286.659510038.19 286.00510048.34287.2085
10058.49285.859510079.45  287.1310089.95288.309110100.46290.608310110.97291.9699
10116.56292.884210121.38 293.49810141.98298.931910152.28300.276310154.49300.9795
#Mann= 3 , 0 , 0
9845.447    0.12       09845.447    0.12       010154.49    0.12       0
#XS Ineff= 2 , 0
       0                               0
Bank Sta=9845.447,10154.49
Exp/Cntr=0.3,0.1

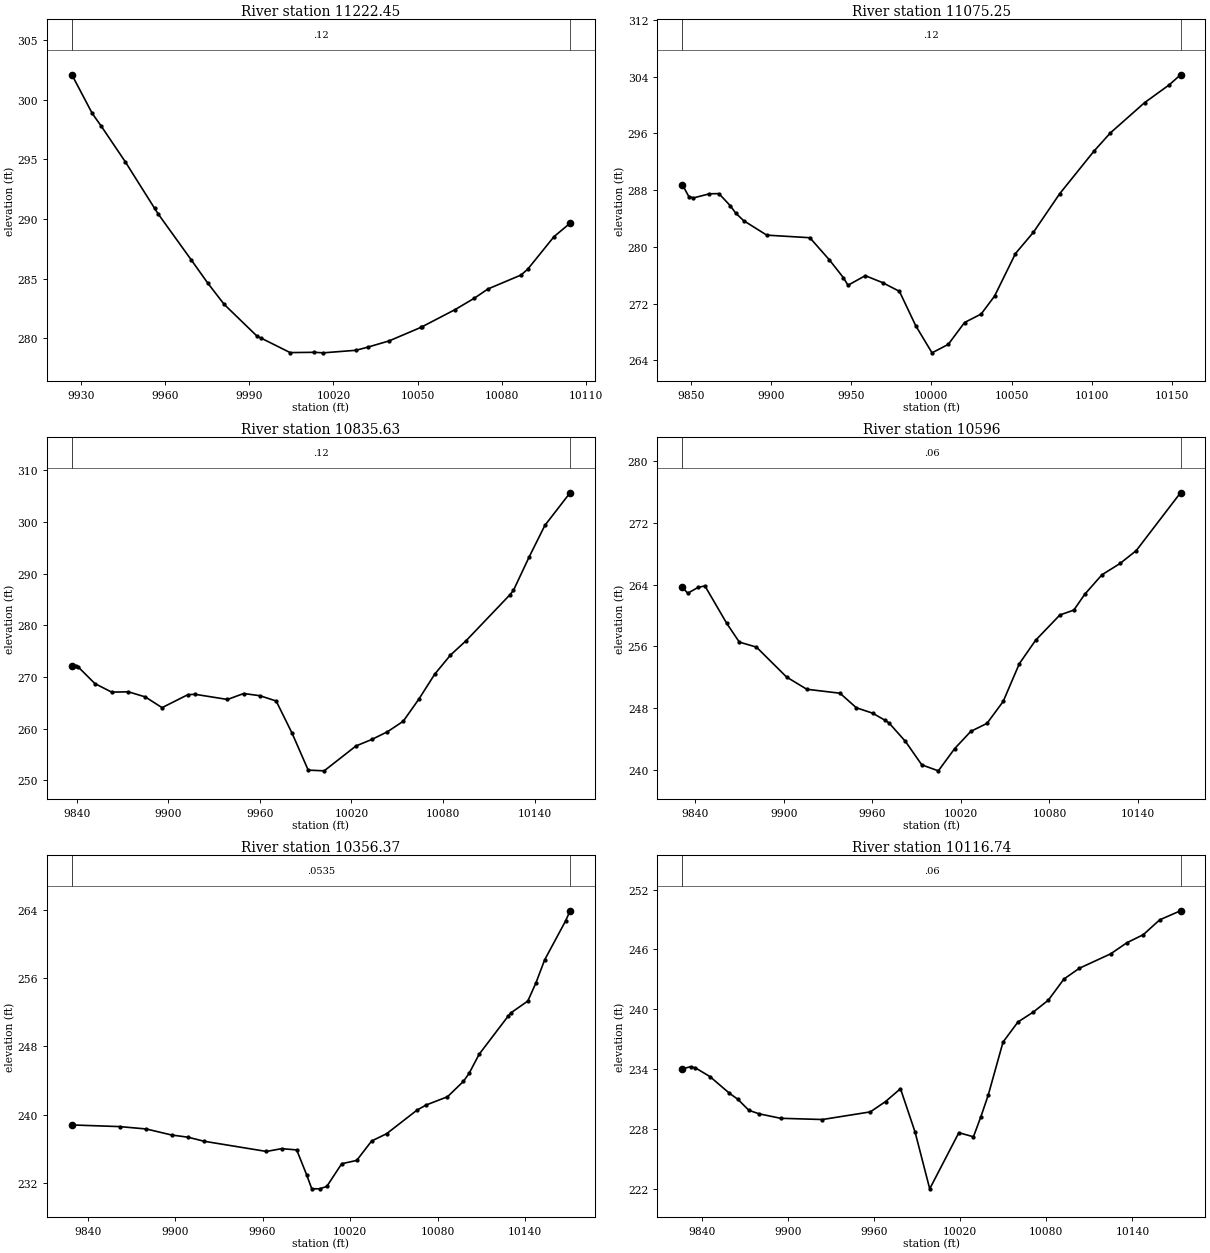
Type RM Length L Ch R = 1 ,11222.45,147.199800,147.199800,147.199800
XS GIS Cut Line= 2
866028.819877774782090.519193515866179.894931167781997.036287546
#Sta/Elev= 26
9926.735302.10599934.002 298.8599937.224297.78649945.762294.80839956.228290.8947
9957.522290.42049969.281286.57299975.233284.60419981.041282.83449992.801280.1556
9994.237279.997810004.56278.785610013.24278.809910016.32278.765410028.08278.9804
10032.25279.243510039.84279.765510051.25280.9085 10051.6280.952810063.36282.3922
10070.25283.351810075.12 284.12910086.88285.295610089.26285.780310098.64288.5149
10104.39289.6485
#Mann= 3 , 0 , 0
9926.735    0.12       09926.735    0.12       010104.39    0.12       0
#XS Ineff= 2 , 0
       0                               0
Bank Sta=9926.735,10104.39
Exp/Cntr=0.3,0.1

Type RM Length L Ch R = 1 ,11075.25,239.628500,239.628500,239.628500
XS GIS Cut Line= 6
866111.880110679 782259.39634281866157.081256963782219.784206272
 866181.15567538782187.682546483866204.392124366782098.413102302
866223.636445947782061.110520727866281.056486755782013.430264146
#Sta/Elev= 30
9844.804288.80219848.828287.10859851.767286.91099861.723287.48999867.605287.5156
9874.618285.82949877.984284.79419882.966283.70929897.417 281.6579924.278281.2929
9936.453278.16549945.161275.66259948.048 274.588 9958.81275.93719969.572274.9601
9980.097273.72719990.253268.8786 10000.4265.051510010.51266.240410020.68269.3312
10031.02270.525910039.37273.054610052.42279.065310063.59282.062310079.92287.4886
10101.23293.486110111.54296.080710132.83300.343910148.33302.881210155.24304.2826
#Mann= 3 , 0 , 0
9844.804    0.12       09844.804    0.12       010155.24    0.12       0
#XS Ineff= 2 , 0
       0                               0
Bank Sta=9844.804,10155.24
Exp/Cntr=0.3,0.1

Type RM Length L Ch R = 1 ,10835.63,239.628500,239.628500,239.628500
XS GIS Cut Line= 6
866131.326425813782386.221455657866192.840006955782357.841018213
866253.013496134782335.839303063866283.935571282782326.005585039
866305.897515585782319.609271224866441.013104149782285.292034887
#Sta/Elev= 30
9836.737272.19389839.653272.16619840.783271.98549851.796268.73989862.809267.0853
9873.822267.14429884.835266.15659895.848264.07949912.755266.5888 9917.43266.6659
9938.725265.66419949.372266.8158 9960.02266.38719970.637265.3665 9981.13 259.088
9991.624251.990410002.11251.852410022.94256.666410033.27257.919110043.58 259.414
 10053.9261.445410064.22265.757710074.54 270.54910084.85274.248110095.17277.0479
10123.84285.920910126.12286.753210136.44293.237610146.76299.347510163.28 305.659
#Mann= 3 , 0 , 0
9836.737    0.12       09836.737    0.12       010163.28    0.12       0
#XS Ineff= 2 , 0
       0                               0
Bank Sta=9836.737,10163.28
Exp/Cntr=0.3,0.1

Type RM Length L Ch R = 1 ,   10596,239.628600,239.628600,239.628600
XS GIS Cut Line= 6
866211.845320773782630.503219562 866253.84832735  782605.3494157
866297.600669176782581.660687277866368.221876208782547.406352185
866448.654419329782511.119439716 866510.73673305782473.971481848
#Sta/Elev= 30
9831.078263.66789834.756262.8696 9841.79263.63299846.412263.81949861.254258.9527
9869.724256.54369881.347255.89039901.774252.01459915.462250.43079937.999249.9144
9949.091248.02989960.184247.32539968.287246.43619971.277246.0561 9982.37243.6704
9993.462240.631710004.67239.857910015.72242.731810026.69244.971610037.66246.0079
10048.63248.848310059.61 253.74910070.58256.767710087.09260.056910096.53260.6854
10103.92262.730110115.57265.256210127.92266.732610138.88268.400210168.87275.8895
#Mann= 3 , 0 , 0
9831.078    0.06       09831.078    0.06       010168.87    0.06       0
#XS Ineff= 2 , 0
       0                               0
Bank Sta=9831.078,10168.87
Exp/Cntr=0.3,0.1

Type RM Length L Ch R = 1 ,10356.37,239.628500,239.628500,239.628500
XS GIS Cut Line= 6
866467.012715136782852.906047182866498.360767412 782805.09682645
866516.677948497782767.663426086866559.633393572782613.932573349
866575.469882668 782576.87773109866596.548214288782539.821799148
#Sta/Elev= 30
9829.245238.77739862.049238.58329880.286238.30339897.656237.59559908.789237.3412
9919.922236.86259962.609235.66779973.064235.99569983.373235.84819990.089232.9613
9993.682231.2933    9999231.280310003.97231.557110014.22234.227410024.48234.6125
10034.74236.8954   10045237.747310065.82240.514810072.05241.114410086.74242.0863
10097.57243.875610101.51244.817310108.44247.073810128.15251.508510130.31251.9401
10141.82253.320610147.43255.470110153.32258.141110167.65262.701710170.78263.9072
#Mann= 3 , 0 , 0
9829.245  0.0535       09829.245  0.0535       010170.78  0.0535       0
#XS Ineff= 2 , 0
       0                               0
Bank Sta=9829.245,10170.78
Exp/Cntr=0.3,0.1

Type RM Length L Ch R = 1 ,10116.74,107.878500,107.878500,107.878500
XS GIS Cut Line= 6
866560.777959237782891.167841976866610.984485523782845.199112003
 866653.62357794782817.674504376866680.585061029782808.235003295
866775.435262049782787.796813477866867.743249725782743.779174766
#Sta/Elev= 30
9826.506234.0209 9832.23 234.2419835.639234.12289845.789233.24519859.347231.5743
9865.256230.96389872.906229.86139880.064229.51129894.915229.06579924.078228.9407
9957.478229.70679968.073 230.7459978.485 232.0319988.664227.67339998.843221.9863
10019.14 227.62110029.29227.206810034.48229.225210039.54231.362410049.92236.7135
10060.29238.723810071.12239.734810081.47 240.91710092.29243.030710103.11244.1199
10124.87245.563410136.26246.684110147.64247.487410159.02248.974310173.53249.8841
#Mann= 3 , 0 , 0
9826.506    0.06       09826.506    0.06       010173.53    0.06       0
#XS Ineff= 2 , 0
       09968.412                       0
Bank Sta=9826.506,10173.53
Exp/Cntr=0.3,0.1

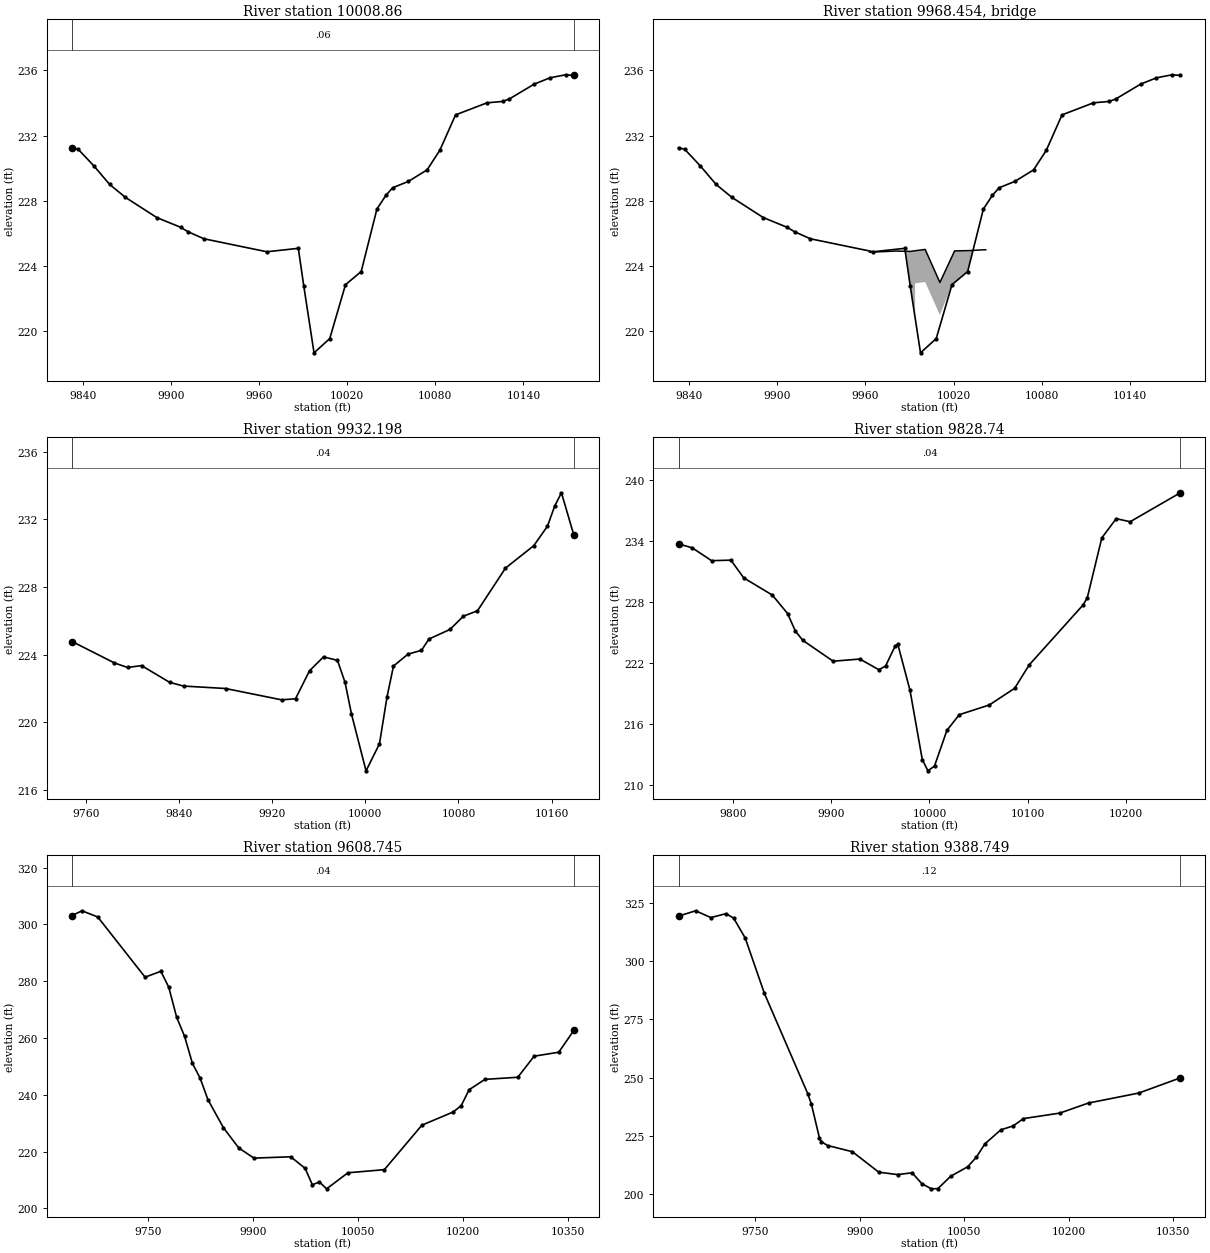
Type RM Length L Ch R = 1 ,10008.86,76.663800,76.663800,76.663800
XS GIS Cut Line= 2
866591.119557232782961.412623018866910.230134159782839.283883691
#Sta/Elev= 30
9832.703231.24839836.857231.15679847.565230.13079858.272228.9955 9868.98228.2028
9890.394226.95899906.598226.36179911.809 226.0839922.516 225.6559965.346224.8567
 9986.76225.0684 9990.53222.72469997.468218.647310008.17219.523410018.88222.8331
10029.59223.6435 10040.3227.486310046.48228.3312   10051228.789310061.71229.1798
10074.46229.887610083.13231.092610093.83 233.26710115.25234.008510125.96234.0926
10130.42234.243910147.37235.156310158.08235.543210168.79235.731110174.39235.6907
#Mann= 3 , 0 , 0
9832.703    0.06       09832.703    0.06       010174.39    0.06       0
#XS Ineff= 2 , 0
       09970.698                       0
Bank Sta=9832.703,10174.39
Exp/Cntr=0.3,0.1

Type RM Length L Ch R = 3 ,9968.454,,,
BEGIN DESCRIPTION:
END DESCRIPTION:
Bridge Culvert--1,0,-1,-1, 0
Deck Dist Width WeirC Skew NumUp NumDn MinLoCord MaxHiCord MaxSubmerge Is_Ogee
28.331900,20.000000,2.6,0, 14, 14, , , 0.95, 0, 0,0,,
 9962.67 9970.59 9980.61 9990.63 9993.79 9993.7910000.6510010.6710018.7910018.79
10020.6910030.7110040.7310041.90
  224.83  224.86  224.90  224.88  224.92  224.92  225.00  222.97  224.54  224.54
  224.91  224.93  224.98  224.98
 -775.17 -775.14 -775.10 -775.12 -775.08  222.92  223.00  220.97  222.54 -775.46
 -775.09 -775.07 -775.02 -775.02
 9962.67 9970.59 9980.61 9989.10 9989.10 9990.6310000.6510010.6710014.1010014.10
10020.6910030.7110040.7310041.90
  224.83  224.86  224.90  224.88  224.88  224.88  225.00  222.97  223.63  223.63
  224.91  224.93  224.98  224.98
 -775.17 -775.14 -775.10 -775.12  222.88  222.88  223.00  220.97  221.63 -776.37
 -775.09 -775.07 -775.02 -775.02
BR Coef=-1 , 0 , 0 ,, 0 ,,,0.8,0,1,0,
WSPro=,,,, 1 ,,,, 0 ,,,, 0 ,,,,-1 ,-1 ,-1 , 0 , 0 , 0 , 0 , 0
BC Design=,, 0 ,, 0 ,,,,,,

Type RM Length L Ch R = 1 ,9932.198,103.457700,103.457700,103.457700
XS GIS Cut Line= 2
866575.361010253783105.209364459866933.867954701782865.876431778
#Sta/Elev= 30
9748.042224.77969784.441223.51369795.703223.24619807.726223.35839831.773222.3708
9843.797222.14869879.868222.00489927.962221.33689939.986 221.3979952.009223.0522
9964.033223.87229976.056223.66679982.558222.3602 9988.08220.494410000.57217.1424
10012.13218.742710018.58221.501310024.15223.331610036.59224.0318 10048.2224.2601
 10054.6224.924610072.61225.490610084.27226.275610096.29226.593710120.34229.1134
10144.65230.438610156.41231.588610162.66232.782410168.43233.5632 10179.1231.0626
#Mann= 3 , 0 , 0
9748.042    0.04       09748.042    0.04       0 10179.1    0.04       0
#XS Ineff= 2 , 0
       09962.843                       0
Bank Sta=9748.042,10179.1
Exp/Cntr=0.3,0.1

Type RM Length L Ch R = 1 , 9828.74,219.995700,219.995700,219.995700
XS GIS Cut Line= 6
 866673.25842122783245.562130591866807.282639507783087.686166494
866858.792512042783019.059186335866878.733973376 782998.81224725
866967.748159078782916.936355077867015.716351452 782868.86910883
#Sta/Elev= 30
9744.904 233.7439758.758233.36189778.498232.09039798.111232.14449811.228230.3935
9840.306228.70049855.758226.88859863.698225.1562 9871.21 224.2479902.113  222.19
9929.285222.40399948.469221.35589955.342221.7075 9964.94223.64369967.798223.8737
9980.255219.31919992.711212.50519998.483211.391910005.15211.865810017.74215.3727
10030.33216.922610060.91217.880910086.63219.5217 10101.4221.821610156.26227.7371
10160.49228.433910175.26234.340310189.91236.230210204.03235.926810255.08 238.779
#Mann= 3 , 0 , 0
9744.904    0.04       09744.904    0.04       010255.08    0.04       0
#XS Ineff= 2 , 0
       09962.345                       0
Bank Sta=9744.904,10255.08
Exp/Cntr=0.3,0.1

Type RM Length L Ch R = 1 ,9608.745,219.995700,219.995700,219.995700
XS GIS Cut Line= 6
866886.476662007 783477.58719985867003.149272378783240.531444047
867019.809556898783187.206780666867040.410431755 783085.23413946
867066.168933548783015.248328024867173.274786481782826.534306432
#Sta/Elev= 30
9641.992303.13549656.157304.81039678.664302.61539746.185281.43499768.692283.4976
9779.946277.90359791.199267.35469802.453260.65829813.706251.10669824.791245.8341
9835.851238.31029857.972228.43619879.828221.31259901.483217.73769954.024 218.195
9974.621214.11229984.807208.36049994.992209.325810005.15206.915310035.63212.5717
10087.57213.664510141.16229.325910186.11234.000410197.34236.239810208.58 241.814
10231.24245.462510277.99246.194310301.36253.618610336.42255.0085   10358262.6954
#Mann= 3 , 0 , 0
9641.992    0.04       09641.992    0.04       0   10358    0.04       0
#XS Ineff= 2 , 0
       0                               0
Bank Sta=9641.992,10358
Exp/Cntr=0.3,0.1

Type RM Length L Ch R = 1 ,9388.749,219.995700,219.995700,219.995700
XS GIS Cut Line= 6
 867026.32703208783557.546752311867129.604419895783348.145952123
867249.120195427783218.766927913867275.436973365783180.543719162
867301.110226455 783111.56073796867347.500424254782927.092319479
#Sta/Elev= 30
9639.558319.20239664.147321.47779685.959318.56119707.771320.25269718.766318.3137
9735.351309.79919762.888286.08999825.241243.09119830.403238.64489842.044224.0694
9844.775222.53679853.685220.92399889.376218.25399927.203209.50589954.121208.4646
9975.136209.23559988.959204.614110002.69202.361510012.13202.452510030.42207.7289
10054.79211.792510067.51215.947610079.62221.617210102.56227.6382 10120.2229.3099
10135.06232.450710187.28234.804610228.52 239.128 10300.7243.388310360.41249.9012
#Mann= 3 , 0 , 0
9639.558    0.12       09639.558    0.12       010360.41    0.12       0
#XS Ineff= 2 , 0
       0                               0
Bank Sta=9639.558,10360.41
Exp/Cntr=0.3,0.1

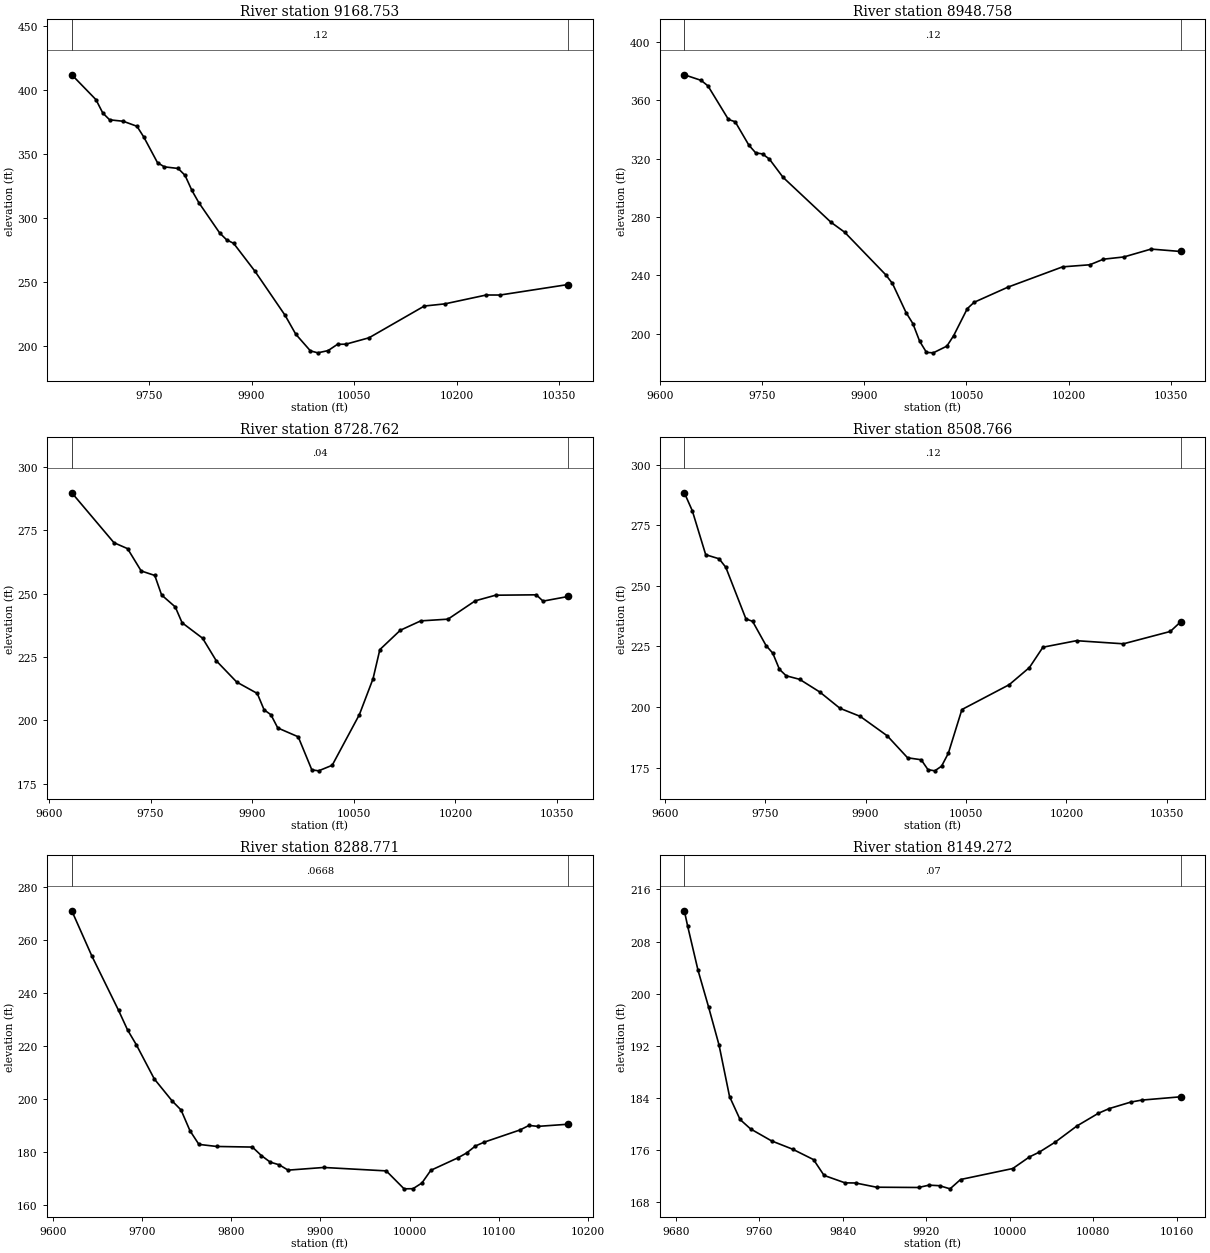
Type RM Length L Ch R = 1 ,9168.753,219.995600,219.995600,219.995600
XS GIS Cut Line= 6
867461.309393861783630.389091925867456.815038187783492.869547216
867439.042860302783387.610677872867337.336215622783201.198139548
867338.152203685783110.795749891867368.418985813782937.334976324
#Sta/Elev= 30
9636.741411.87949672.131392.47139682.132382.05199692.132376.75759712.133 375.622
9732.168371.71219742.188363.28589762.228343.31379772.247340.07979792.403338.8333
9802.487333.48889812.572321.70129822.657312.20949853.181288.55959863.422283.1661
9873.664  280.449905.044 258.5669949.008224.28419964.615209.59819986.017196.6009
9996.822195.047410011.94196.795710025.72 201.69410038.01201.8007 10071.9206.7908
 10152.8231.541910182.88233.2298 10243.5240.149510263.72240.128310363.23248.3164
#Mann= 3 , 0 , 0
9636.741    0.12       09636.741    0.12       010363.23    0.12       0
#XS Ineff= 2 , 0
       0                               0
Bank Sta=9636.741,10363.23
Exp/Cntr=0.3,0.1

Type RM Length L Ch R = 1 ,8948.758,219.995700,219.995700,219.995700
XS GIS Cut Line= 6
867614.708044588783619.629582209867607.737538143783510.903202733
867588.415185467783305.708004468867588.161629657783183.385632429
867582.402267599 783007.42289434867584.166975543782891.666225344
#Sta/Elev= 30
9635.384377.33499660.064373.50729670.085369.72399700.147346.78119710.167345.1515
9730.208329.17139740.229323.91529750.268 323.1599760.321319.65659780.427307.1626
9850.797276.42949870.903269.6228 9931.12240.56479941.144234.56679961.167214.6163
9971.168207.08849981.168195.00379991.169 187.35310001.17187.048910021.17191.6455
10031.17198.845510051.17217.285810061.17221.633510111.19232.063110191.24245.8985
10231.26247.316610251.27251.136310281.27252.668910321.28258.058110364.62 256.413
#Mann= 3 , 0 , 0
9635.384    0.12       09635.384    0.12       010364.62    0.12       0
#XS Ineff= 2 , 0
       0                               0
Bank Sta=9635.384,10364.62
Exp/Cntr=0.3,0.1

Type RM Length L Ch R = 1 ,8728.762,219.995700,219.995700,219.995700
XS GIS Cut Line= 6
867843.769088227783576.974971417867831.759294144783448.084025817
867806.627869335783258.478467962867783.610746233783026.853652896
867776.763156106782940.706887131867773.645029905782848.099795705
#Sta/Elev= 30
9633.712289.72819695.955270.05799716.042 267.7159736.129258.92949756.215257.1504
9766.272249.46179786.447244.74129796.535238.51389826.797232.42029846.972 223.537
9877.234215.13229907.497 210.6669917.584204.20489927.672202.26629937.759197.0646
9967.953193.57429988.026180.56299998.062180.162910018.13182.358410058.28202.3422
 10078.4216.441410088.46227.929810118.65235.559610148.83239.250410189.07239.9327
 10229.2 247.14510259.29249.367810319.36249.519510329.37247.036510366.29248.8586
#Mann= 3 , 0 , 0
9633.712    0.04       09633.712    0.04       010366.29    0.04       0
#XS Ineff= 2 , 0
       0                               0
Bank Sta=9633.712,10366.29
Exp/Cntr=0.3,0.1

Type RM Length L Ch R = 1 ,8508.766,219.995700,219.995700,219.995700
XS GIS Cut Line= 6
868056.932801841 783546.86828163868050.284075132783420.441392906
868040.794140606783317.443558951868006.470633756783099.486952093
867995.883651156783009.804019742867986.103812851782809.636202767
#Sta/Elev= 30
9629.261288.38189641.146 280.9779661.173262.83989681.201261.16059691.215257.6455
9721.256 236.383 9731.27235.35019751.298225.39749761.327222.26329771.369215.5736
9781.412212.91149801.497211.44679831.624206.21789861.762 199.501 9892.03196.1675
9932.388188.15729962.825179.08729983.122178.2788 9993.27174.208110003.41173.7075
10013.55175.619210023.69180.949510043.97198.9871 10114.7209.2415 10144.9216.3239
10165.04224.694610215.19227.382910285.34226.096110355.36231.190810370.73235.1409
#Mann= 3 , 0 , 0
9629.261    0.12       09629.261    0.12       010370.73    0.12       0
#XS Ineff= 2 , 0
       0                               0
Bank Sta=9629.261,10370.73
Exp/Cntr=0.3,0.1

Type RM Length L Ch R = 1 ,8288.771,139.498400,139.498400,139.498400
XS GIS Cut Line= 5
 868226.73415643783547.462775797868238.791046739783169.855636016
868238.845734209 783167.85638386 868242.62781629783052.291976213
868245.501136571 782991.24980855
#Sta/Elev= 30
  9621.2271.05789643.675253.9864 9673.69233.39369683.695226.0638  9693.7220.3521
 9713.71207.52269733.721199.21569743.726195.78499753.731187.95279763.736182.7841
9783.746181.99929823.766181.76859833.771178.56589843.777176.07069853.782175.0724
9863.787173.05269903.807174.06369973.843172.76789993.853165.987210003.86166.0391
10013.86168.199610023.87172.995110053.88177.653410063.89179.5132 10073.9 182.186
 10083.9183.652310123.93188.244310133.94189.947510143.95189.591510177.74190.4011
#Mann= 3 , 0 , 0
  9621.2  0.0668       0  9621.2  0.0668       010177.74  0.0668       0
#XS Ineff= 2 , 0
       09890.493        10129.67       0
Bank Sta=9621.2,10177.74
Exp/Cntr=0.3,0.1

Type RM Length L Ch R = 1 ,8149.272,124.501600,124.501600,124.501600
XS GIS Cut Line= 4
868349.149218142783488.053073943868379.142233342783221.644527256
 868377.37793833783159.012054339868341.209890634783018.750600949
#Sta/Elev= 30
 9688.21212.71289691.283210.42939701.346203.56999711.409197.97259721.472 192.116
9731.535184.22149741.598 180.7059751.662  179.269771.788177.42059791.914176.1524
9812.041174.54849822.104172.1276 9842.23170.98589852.293170.9656 9872.42170.3169
9912.672170.27479922.736170.63419932.799170.54859942.862170.06769952.925171.4975
10002.96173.182810018.96174.964610028.48175.705510043.76177.244510064.41179.7076
10085.07181.662110095.39 182.37610116.05183.370710126.37183.674410163.81184.1829
#Mann= 3 , 0 , 0
 9688.21    0.07       0 9688.21    0.07       010163.81    0.07       0
#XS Ineff= 2 , 0
       09851.147        10099.43       0
Bank Sta=9688.21,10163.81
Exp/Cntr=0.3,0.1