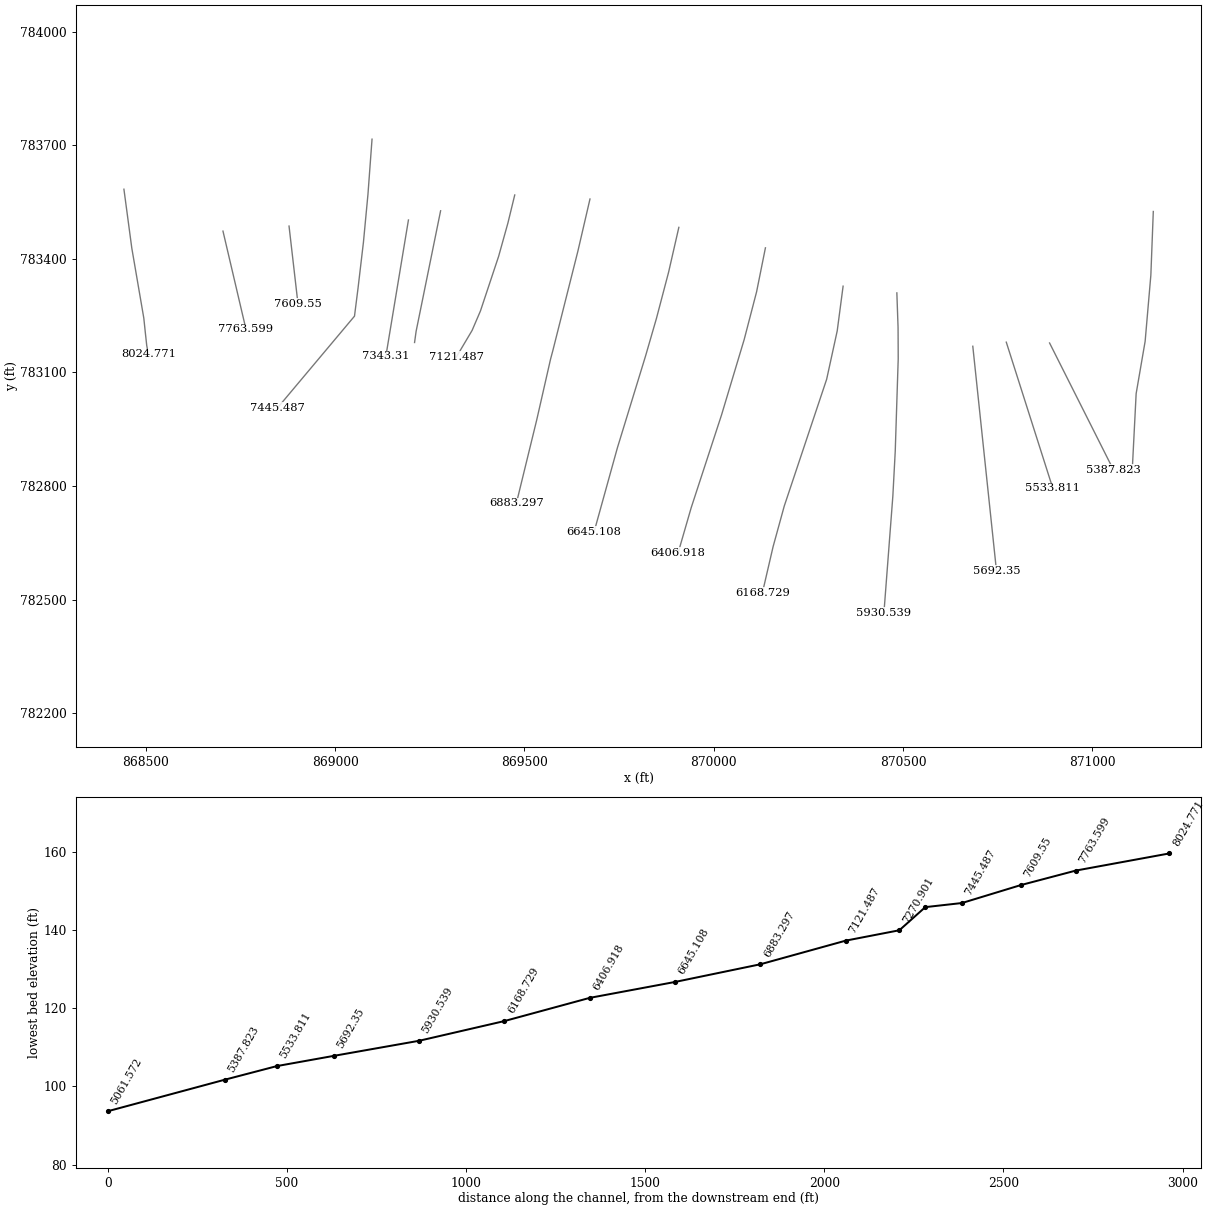
HEC-RAS study 11666_ras.prj: 11666

--- 11666_ras.g01 (geometry) --- (continued)

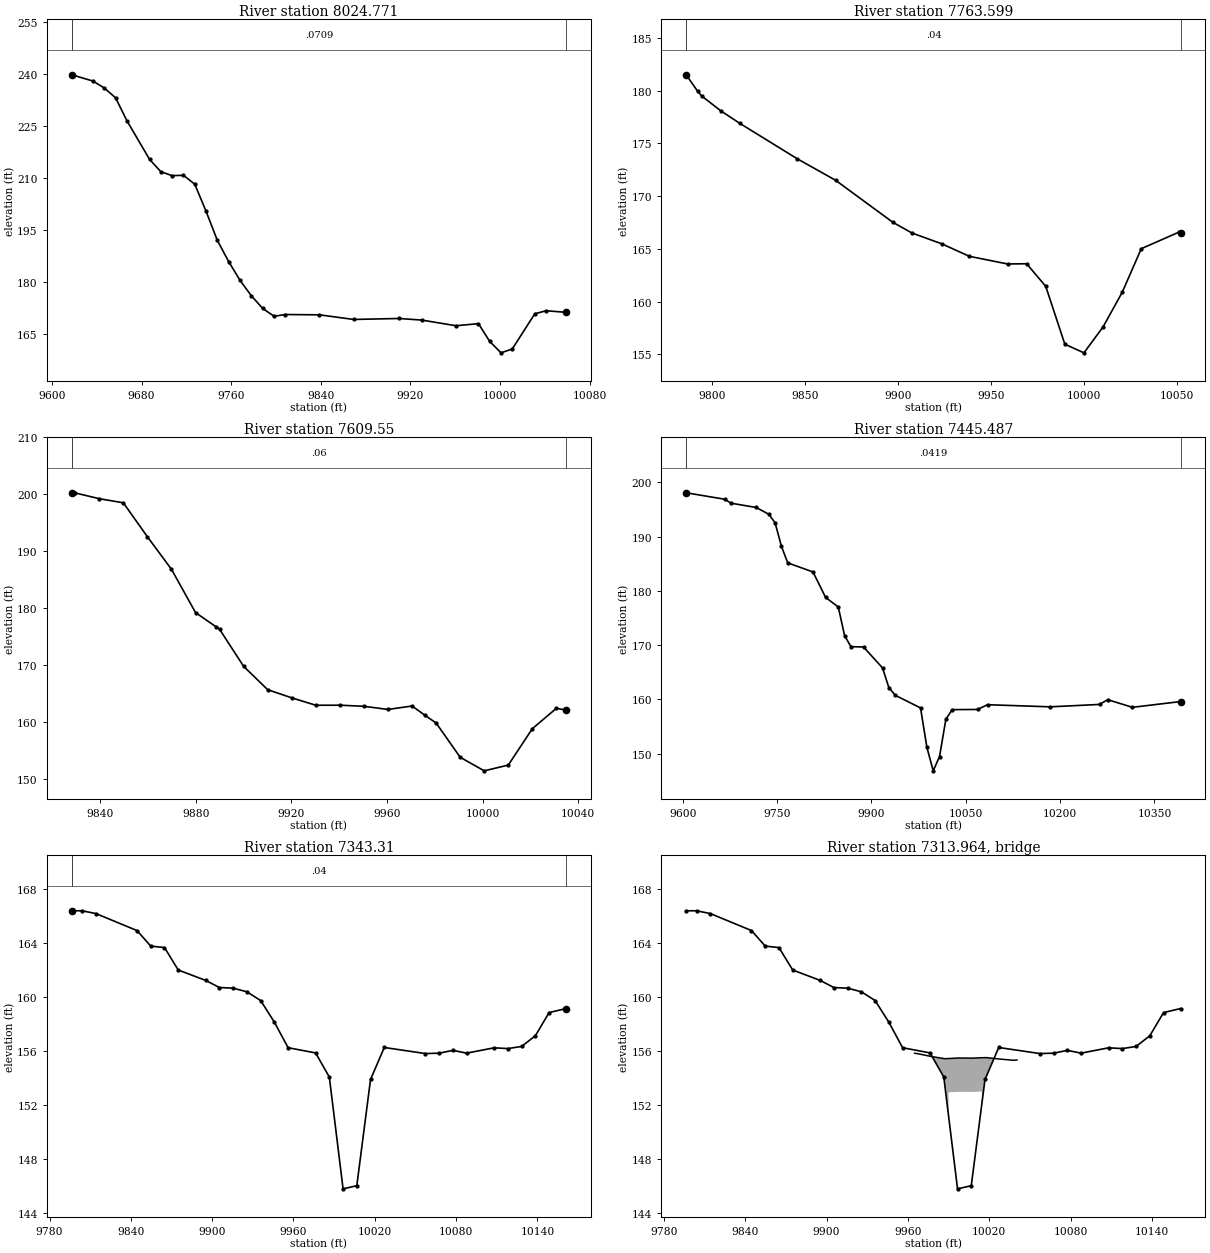
Type RM Length L Ch R = 1 ,8024.771,261.171900,261.171900,261.171900
XS GIS Cut Line= 6
868441.986712307783583.837211907868462.792175651783428.201548666
868494.487990081783243.411331728868498.543947697783204.794058517
868502.161698788 783171.50845173  868506.4976798783147.379036993
#Sta/Elev= 30
 9617.66239.72339636.665237.91189646.754235.90219656.843233.07049666.932226.4645
 9687.11215.34129697.199211.77999707.287210.62899717.376210.73729727.465208.1752
9737.554200.37229747.643191.96429757.732185.85519767.821180.47689777.928176.0107
9788.075172.35929798.221170.08139808.367170.58719838.805170.49329869.243169.1647
9909.827169.44379930.119168.98299960.557167.35299980.685167.94939990.742162.8173
10000.79159.536310010.85160.655710030.97170.801810041.09 171.677   10059 171.214
#Mann= 3 , 0 , 0
 9617.66  0.0709       0 9617.66  0.0709       0   10059  0.0709       0
#XS Ineff= 2 , 0
       09890.699                       0
Bank Sta=9617.66,10059
Exp/Cntr=0.3,0.1

Type RM Length L Ch R = 1 ,7763.599,154.048600,154.048600,154.048600
XS GIS Cut Line= 2
868703.597968519783473.155856997868764.227074057783214.373089567
#Sta/Elev= 21
9786.308181.49269792.455179.93599794.685179.47789804.956178.07349815.227176.8792
9846.039173.5323 9866.58171.50259897.393167.51619907.664166.50269923.971165.4588
9938.476164.29599959.017163.56959969.288163.58959979.559161.4537 9989.83155.9698
 10000.1155.149610010.37157.602610020.64 160.87210030.91165.015210051.45166.6073
 10052.1166.5417
#Mann= 3 , 0 , 0
9786.308    0.04       09786.308    0.04       0 10052.1    0.04       0
#XS Ineff= 2 , 0
       0                               0
Bank Sta=9786.308,10052.1
Exp/Cntr=0.3,0.1

Type RM Length L Ch R = 1 , 7609.55,164.063300,164.063300,164.063300
XS GIS Cut Line= 2
868878.091491699783486.464685038868901.751630425783280.917229757
#Sta/Elev= 25
9828.128200.24849829.602200.21889839.668 199.2099849.734198.4874  9859.8192.5265
9869.866186.81719879.932179.21529888.541176.71489889.998176.28139900.064169.7741
 9910.13 165.6739920.196164.24369930.262162.94449940.328162.95339950.394162.7608
 9960.46162.20589970.526162.8145 9975.99161.15859980.592159.82969990.658153.8139
10000.72151.428110010.79  152.4410020.86 158.83610030.92162.403410035.03162.0928
#Mann= 3 , 0 , 0
9828.128    0.06       09828.128    0.06       010035.03    0.06       0
#XS Ineff= 2 , 0
       0                               0
Bank Sta=9828.128,10035.03
Exp/Cntr=0.3,0.1

Type RM Length L Ch R = 1 ,7445.487,102.176600,102.176600,102.176600
XS GIS Cut Line= 6
869097.297436833783716.025674522869086.558700889783570.492167741
869074.586390913783443.609262034869060.302363843783322.142751381
869050.976519793783248.511279047868847.543683052783006.142880008
#Sta/Elev= 30
9605.321198.05679666.512196.86799676.539196.14169716.648195.35179736.703194.1019
 9746.73192.53339756.766188.20159766.811 185.1499806.988183.47439827.077178.7783
9847.166177.02729857.211171.76299867.255169.71689887.365169.66359917.573165.7939
9927.642162.17469937.711160.76669977.988158.43769988.057151.20329998.126146.8523
 10008.2  149.4910018.28 156.36610028.36158.121110068.68158.155510084.52159.0295
10184.25158.639210262.58159.081510275.64159.955910314.81158.551310391.65159.6122
#Mann= 3 , 0 , 0
9605.321  0.0419       09605.321  0.0419       010391.65  0.0419       0
#XS Ineff= 2 , 0
       0                10116.73       0
Bank Sta=9605.321,10391.65
Exp/Cntr=0.3,0.1

Type RM Length L Ch R = 1 , 7343.31,72.409700,72.409700,72.409700
XS GIS Cut Line= 2
869193.469248623783502.553008631869133.803115308783142.533628106
#Sta/Elev= 30
9796.384166.3678 9804.04166.36869814.176166.16389844.586164.90539854.722163.7555
9864.858163.64779874.995161.98949895.268161.21799905.404160.6908 9915.54160.6466
9925.677160.37649935.813 159.731 9945.95158.12849956.086156.24169976.359 155.856
9986.495154.07329996.632145.803910006.77 146.035 10016.9153.892710027.04156.2577
10057.45155.808510067.59155.837410077.72156.044410087.86155.839610108.13156.2347
10118.27156.1771 10128.4156.334210138.54157.127310148.68158.839910161.31  159.14
#Mann= 3 , 0 , 0
9796.384    0.04       09796.384    0.04       010161.31    0.04       0
#XS Ineff= 2 , 0
       0                               0
Bank Sta=9796.384,10161.31
Exp/Cntr=0.3,0.1

Type RM Length L Ch R = 3 ,7313.964,,,
BEGIN DESCRIPTION:
END DESCRIPTION:
Bridge Culvert--1,0,-1,-1, 0
Deck Dist Width WeirC Skew NumUp NumDn MinLoCord MaxHiCord MaxSubmerge Is_Ogee
19.474850,33.460000,2.6,0, 16, 16, , , 0.95, 0, 0,0,,
 9964.94 9966.57 9967.24 9976.80 9987.04 9990.02 9990.02 9997.2810007.5110013.94
10014.6210014.6210017.7510027.9910038.2310040.52
  155.83  155.81  155.80  155.60  155.43  155.44  155.44  155.48  155.47  155.50
  155.50  155.50  155.51  155.40  155.31  155.34
 -844.17 -844.19 -844.20 -844.40 -844.57 -844.56  152.94  152.98  152.97  153.00
  153.00 -844.50 -844.49 -844.60 -844.69 -844.66
 9964.94 9966.57 9967.24 9976.80 9981.00 9981.00 9987.04 9997.2810005.6010005.60
10007.5110013.9410017.7510027.9910038.2310040.52
  155.83  155.81  155.80  155.60  155.53  155.53  155.43  155.48  155.47  155.47
  155.47  155.50  155.51  155.40  155.31  155.34
 -844.17 -844.19 -844.20 -844.40 -844.47  153.03  152.93  152.98  152.97 -844.53
 -844.53 -844.50 -844.49 -844.60 -844.69 -844.66
BR Coef=-1 , 0 , 0 ,, 0 ,,,0.8,0,1,0,
WSPro=,,,, 1 ,,,, 0 ,,,, 0 ,,,,-1 ,-1 ,-1 , 0 , 0 , 0 , 0 , 0
BC Design=,, 0 ,, 0 ,,,,,,

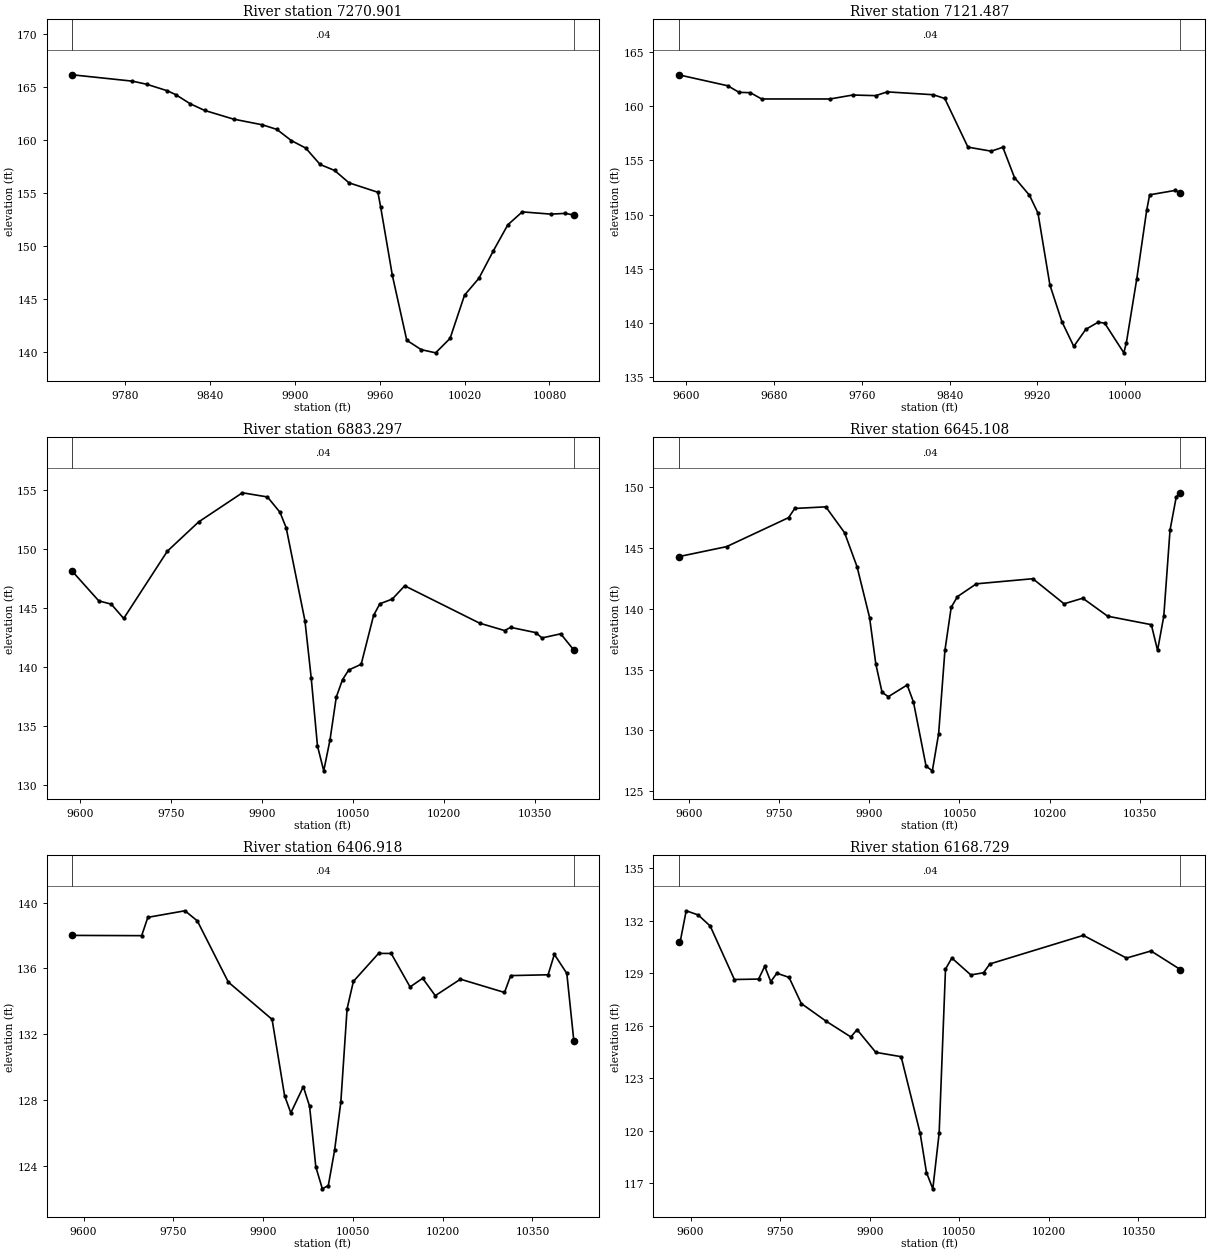
Type RM Length L Ch R = 1 ,7270.901,149.413700,149.413700,149.413700
XS GIS Cut Line= 3
869278.417641759783526.823978111869213.695056498783208.267503768
869209.649894923783178.940082312
#Sta/Elev= 30
9742.564166.17749785.243165.57469795.447165.27739809.954164.66239815.856164.2988
 9826.06163.43719836.264162.80789856.673161.98529877.082161.44739887.286161.0144
 9897.49159.96139907.695  159.259917.899157.69569928.103157.13359938.307155.9627
9958.716155.06929960.627153.7126 9968.92147.22579979.125141.07829989.329140.1925
9999.533139.889510009.74141.255410019.94 145.33810030.15 146.94510040.35149.5381
10050.55151.993110060.76153.216210081.02153.002810091.12153.073710097.23152.9174
#Mann= 3 , 0 , 0
9742.564    0.04       09742.564    0.04       010097.23    0.04       0
#XS Ineff= 2 , 0
       0                               0
Bank Sta=9742.564,10097.23
Exp/Cntr=0.3,0.1

Type RM Length L Ch R = 1 ,7121.487,238.189500,238.189500,238.189500
XS GIS Cut Line= 6
869474.221209826783568.565721126869456.208176309783494.581053689
869431.723328762783406.718811101869383.602808516783262.124380799
869361.563604598783210.757712394869319.972412409783140.614953538
#Sta/Elev= 30
9592.904162.89549637.743161.88229648.035161.27629658.327161.24369668.619 160.665
9730.902 160.6629751.664161.02829772.551160.97089783.039161.31769824.992 161.055
 9835.48160.71039856.625156.22019877.824155.84779888.424156.20899899.023 153.415
9912.671151.78089920.423150.14199931.305143.50359942.186140.13429953.068137.8391
 9963.95139.40449975.293140.0735 9981.26139.97929998.658137.2437   10001138.1869
10010.45144.061410019.51150.4043 10022.2151.820810045.22152.223710050.15152.0197
#Mann= 3 , 0 , 0
9592.904    0.04       09592.904    0.04       010050.15    0.04       0
#XS Ineff= 2 , 0
       0                               0
Bank Sta=9592.904,10050.15
Exp/Cntr=0.3,0.1

Type RM Length L Ch R = 1 ,6883.297,238.189500,238.189500,238.189500
XS GIS Cut Line= 6
869672.956254331783557.904404667869641.027171823 783420.22485008
869574.770471024783157.174360049869568.878204914783135.155454122
869532.219347286782974.138668427869478.441943143782753.935411868
#Sta/Elev= 30
  9586.4148.12049630.443145.59359650.974145.31889671.505144.10349743.434149.8006
9794.996152.27789867.182154.74739908.431154.39459929.056153.10269939.368151.7865
9970.305143.90769980.618 139.075 9990.93133.318810001.26131.202610011.61133.8209
10021.95137.446210032.21138.919710042.47139.742110062.98140.225810083.49144.3648
10093.74 145.34710114.26145.747410134.77146.8709 10258.1143.710210299.28143.0832
10309.57143.350310350.75142.907310361.04142.454210391.92142.804410413.61141.4275
#Mann= 3 , 0 , 0
  9586.4    0.04       0  9586.4    0.04       010413.61    0.04       0
#XS Ineff= 2 , 0
       0                               0
Bank Sta=9586.4,10413.61
Exp/Cntr=0.3,0.1

Type RM Length L Ch R = 1 ,6645.108,238.189500,238.189500,238.189500
XS GIS Cut Line= 6
869907.687170198783483.081531478869880.613925294783364.664121619
869848.460256406783242.374493657869819.645514535783142.933950392
869745.320335804782900.595598588869683.728290731782678.473239669
#Sta/Elev= 30
9582.282144.29769662.379145.12529765.447 147.5089775.787148.26539827.487148.3973
9858.702146.27219879.525143.46669900.347139.29329910.759135.4628 9921.17133.1356
9931.581132.78279962.986 133.7459973.458132.33599994.402127.068210004.87126.6817
10015.33129.743510025.78136.580710036.24140.132410046.69141.013210078.06142.0651
10172.15142.485610224.15140.422210255.28140.882110296.79139.401210369.43138.7057
10379.81136.591910390.19139.405410400.57146.483210410.94 149.21610417.72149.5546
#Mann= 3 , 0 , 0
9582.282    0.04       09582.282    0.04       010417.72    0.04       0
#XS Ineff= 2 , 0
       0                               0
Bank Sta=9582.282,10417.72
Exp/Cntr=0.3,0.1

Type RM Length L Ch R = 1 ,6406.918,238.189500,238.189500,238.189500
XS GIS Cut Line= 6
870136.374366863 783429.00367838 870113.03453343783312.818730089
 870080.19017399783186.533198524 870020.35357729782987.350486189
869940.327045488782742.669656333 869905.86005954782623.687360238
#Sta/Elev= 30
 9580.87138.00289697.151137.98679707.454139.09919769.451139.49779790.116138.8845
9841.905135.16759914.996132.90499935.879128.2713 9946.32127.22539967.203128.8206
9977.645127.62769988.087123.9432    9999122.614110008.95122.8156 10019.4124.9442
10029.85127.878910040.31 133.54610050.83135.210910092.92136.910610113.96136.9054
10145.53134.873410166.57135.398910187.61134.3422 10229.7135.344310303.26134.5381
10313.67135.561610376.14135.611710386.55136.851510407.37135.695610419.15131.5879
#Mann= 3 , 0 , 0
 9580.87    0.04       0 9580.87    0.04       010419.15    0.04       0
#XS Ineff= 2 , 0
       0                               0
Bank Sta=9580.87,10419.15
Exp/Cntr=0.3,0.1

Type RM Length L Ch R = 1 ,6168.729,238.189500,238.189500,238.189500
XS GIS Cut Line= 6
870341.534882745783327.753514699870325.978408489783209.588056833
870298.135298391783082.021043976870186.067157573782746.843331203
870156.598250304782639.577730665870128.195636515782517.188593012
#Sta/Elev= 30
9579.914130.77529582.684130.79049592.746132.5552 9612.87132.31659632.994131.6816
9673.424128.63269713.989128.65689724.181129.38619734.374128.51079744.566128.9909
9764.951128.75399785.458 127.2639826.658126.26069868.413125.35489878.863 125.771
9910.213124.47449952.627124.2278 9984.46119.86019995.071117.616410005.68116.6845
10016.29119.870510026.91129.226610037.52129.858410069.36128.893410090.59 129.018
10101.14129.520610257.72131.151710329.95129.856210371.01130.2615 10420.1129.2026
#Mann= 3 , 0 , 0
9579.914    0.04       09579.914    0.04       0 10420.1    0.04       0
#XS Ineff= 2 , 0
       0                               0
Bank Sta=9579.914,10420.1
Exp/Cntr=0.3,0.1

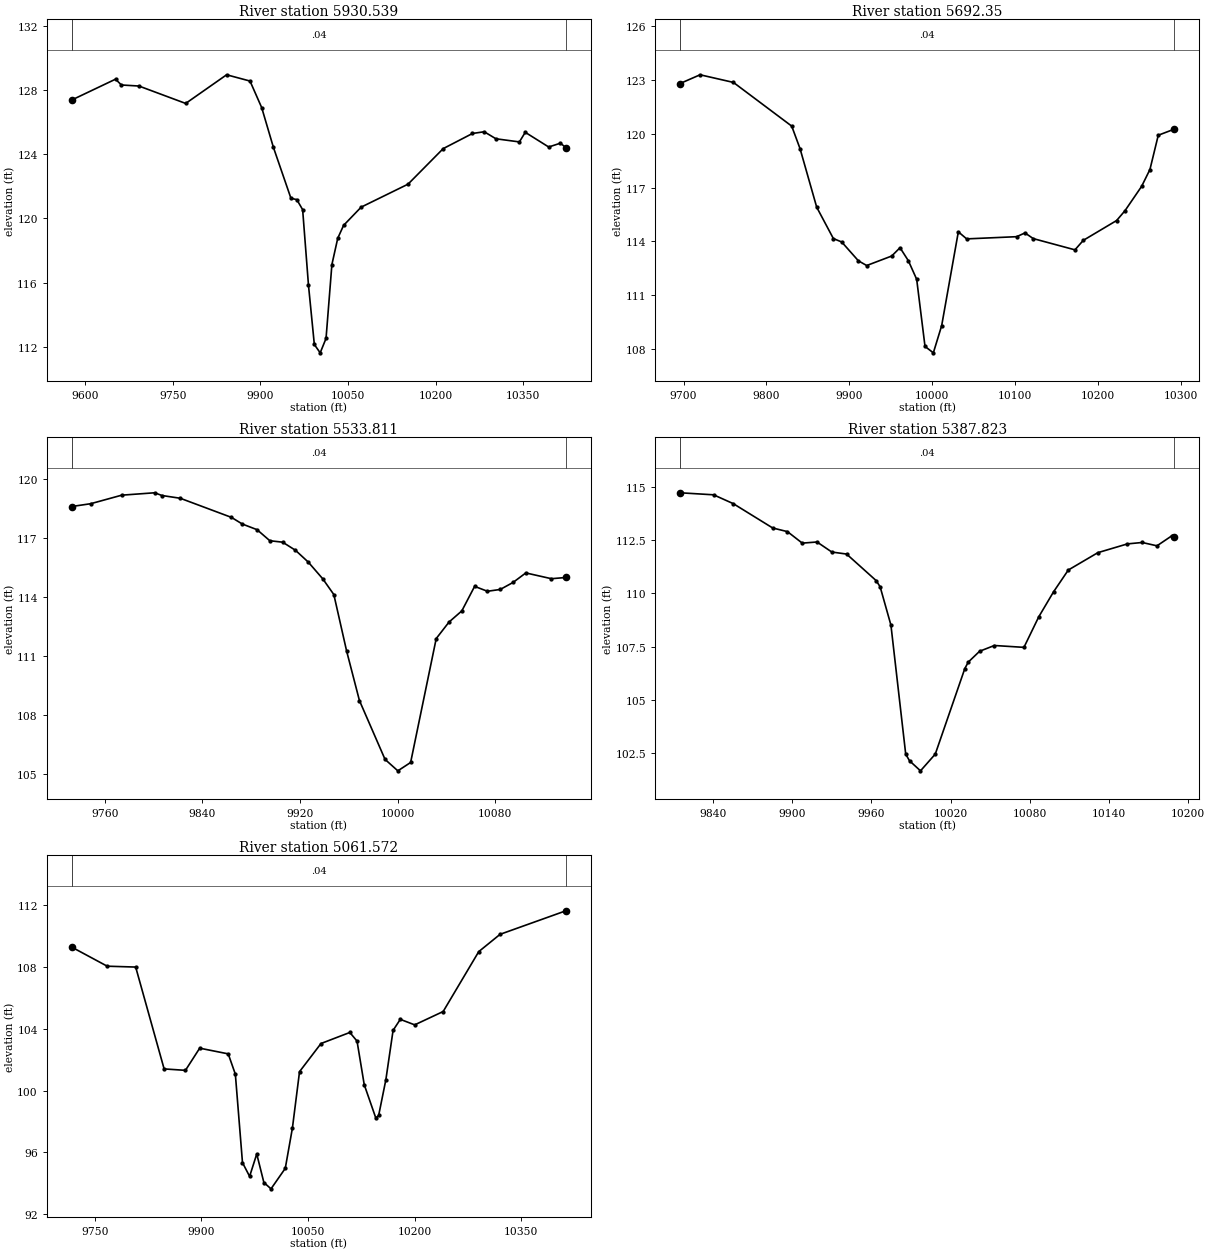
Type RM Length L Ch R = 1 ,5930.539,238.189500,238.189500,238.189500
XS GIS Cut Line= 6
 870483.51105012783309.973466255870486.717894635783218.143794712
870487.114911243783136.106975226870479.246120562782891.785056295
870472.905263001782772.993859928870449.402480744782465.674026963
#Sta/Elev= 30
9577.228127.36919652.247128.66639662.253128.30499692.257128.24059772.269127.1573
9842.305128.94019882.326128.54989902.336126.89529922.347 124.4269952.362121.2569
9962.367121.17469972.373120.54999982.378115.84389992.383112.162110002.39111.6423
10012.41112.540410022.42117.132410032.44118.771810042.45119.571810072.49120.7063
10152.67122.134410212.84124.345910262.99 125.28910283.04125.3956 10303.1124.9583
10343.22124.763710353.25125.360810393.37124.447110413.42124.684910422.78124.4084
#Mann= 3 , 0 , 0
9577.228    0.04       09577.228    0.04       010422.78    0.04       0
#XS Ineff= 2 , 0
       0                               0
Bank Sta=9577.228,10422.78
Exp/Cntr=0.3,0.1

Type RM Length L Ch R = 1 , 5692.35,158.539300,158.539300,158.539300
XS GIS Cut Line= 2
 870684.09707731783169.044564858870746.657270551782575.801353112
#Sta/Elev= 30
9695.826122.80319720.003  123.299760.225122.86439830.613120.42719840.669119.1681
 9860.78115.90379880.891114.15679890.946113.96649911.057112.91819921.112112.6529
9951.279113.18339961.334113.6472 9971.39112.92189981.445111.88559991.501108.1421
10001.56107.784710011.61109.301310031.72114.532310041.78114.138810102.11114.2616
10112.17114.471210122.22 114.154 10172.5113.527910182.55114.056910222.78115.1628
10232.83115.707410252.94117.0664   10263118.007910273.05119.918710292.36120.2574
#Mann= 3 , 0 , 0
9695.826    0.04       09695.826    0.04       010292.36    0.04       0
#XS Ineff= 2 , 0
       0                10075.34       0
Bank Sta=9695.826,10292.36
Exp/Cntr=0.3,0.1

Type RM Length L Ch R = 1 ,5533.811,145.987800,145.987800,145.987800
XS GIS Cut Line= 2
870772.544247091783179.830805078870895.507385552782793.683405429
#Sta/Elev= 30
9732.791118.60329748.355118.74549773.841119.17949800.829119.30089806.799119.1623
9821.818119.02239863.798118.05099872.713117.71339884.787117.42679895.282116.8653
9905.777116.79169916.271116.38139926.766115.78179938.628114.93369947.756114.1311
 9958.25111.25869968.745108.74779989.735105.760610000.23105.177810010.72105.6024
10031.71111.896710042.21112.7348 10052.7113.3012 10063.2114.547610073.69114.2985
10084.19114.390110094.68114.745510105.18  115.2310126.17114.936310138.04114.9986
#Mann= 3 , 0 , 0
9732.791    0.04       09732.791    0.04       010138.04    0.04       0
#XS Ineff= 2 , 0
       0                               0
Bank Sta=9732.791,10138.04
Exp/Cntr=0.3,0.1

Type RM Length L Ch R = 1 ,5387.823,326.250700,326.250700,326.250700
XS GIS Cut Line= 2
870886.878393352783177.673557028871055.143740714  782843.3001104
#Sta/Elev= 30
9815.069114.71319840.452114.61799855.383114.20389885.231113.06329896.426112.8921
9907.621112.35389918.815112.4067 9930.01111.93649941.205111.84149963.595110.5976
9966.613110.30689974.789108.51139985.984102.46549988.859102.15519997.179101.6825
10008.37102.466510030.76106.476410033.35106.777410041.96107.286510053.15107.5561
10075.54107.469210086.74108.898310097.93110.068610109.13111.092910131.52111.9071
10153.91112.3176 10165.1112.3838 10176.3112.227210187.49112.694410189.39112.6389
#Mann= 3 , 0 , 0
9815.069    0.04       09815.069    0.04       010189.39    0.04       0
#XS Ineff= 2 , 0
       0                               0
Bank Sta=9815.069,10189.39
Exp/Cntr=0.3,0.1

Type RM Length L Ch R = 1 ,5061.572,130.592500,130.592500,130.592500
XS GIS Cut Line= 5
871160.848894805783524.990491912871154.377150685783356.725144595
871139.276414335783181.988053113871115.546685874783043.924178377
871104.760445654782832.513870195
#Sta/Elev= 30
9717.384109.29749767.412108.05929807.441108.00419847.471101.40289877.493101.3107
9897.543102.74729937.692102.37829947.729101.06089957.76795.328159967.80494.43783
9977.84195.889879987.87894.040879997.91693.6310510017.9994.9591210028.0397.56849
10038.06101.225310068.25 103.04810108.84103.765210118.99103.206110129.13100.3793
10145.4498.2179510149.4398.3914110159.57100.702910169.72103.901310179.87104.6143
10200.16104.258210240.23105.123410290.29109.003910320.33110.125810412.94111.6513
#Mann= 3 , 0 , 0
9717.384    0.04       09717.384    0.04       010412.94    0.04       0
#XS Ineff= 2 , 0
       09936.193        10064.72       0
Bank Sta=9717.384,10412.94
Exp/Cntr=0.3,0.1