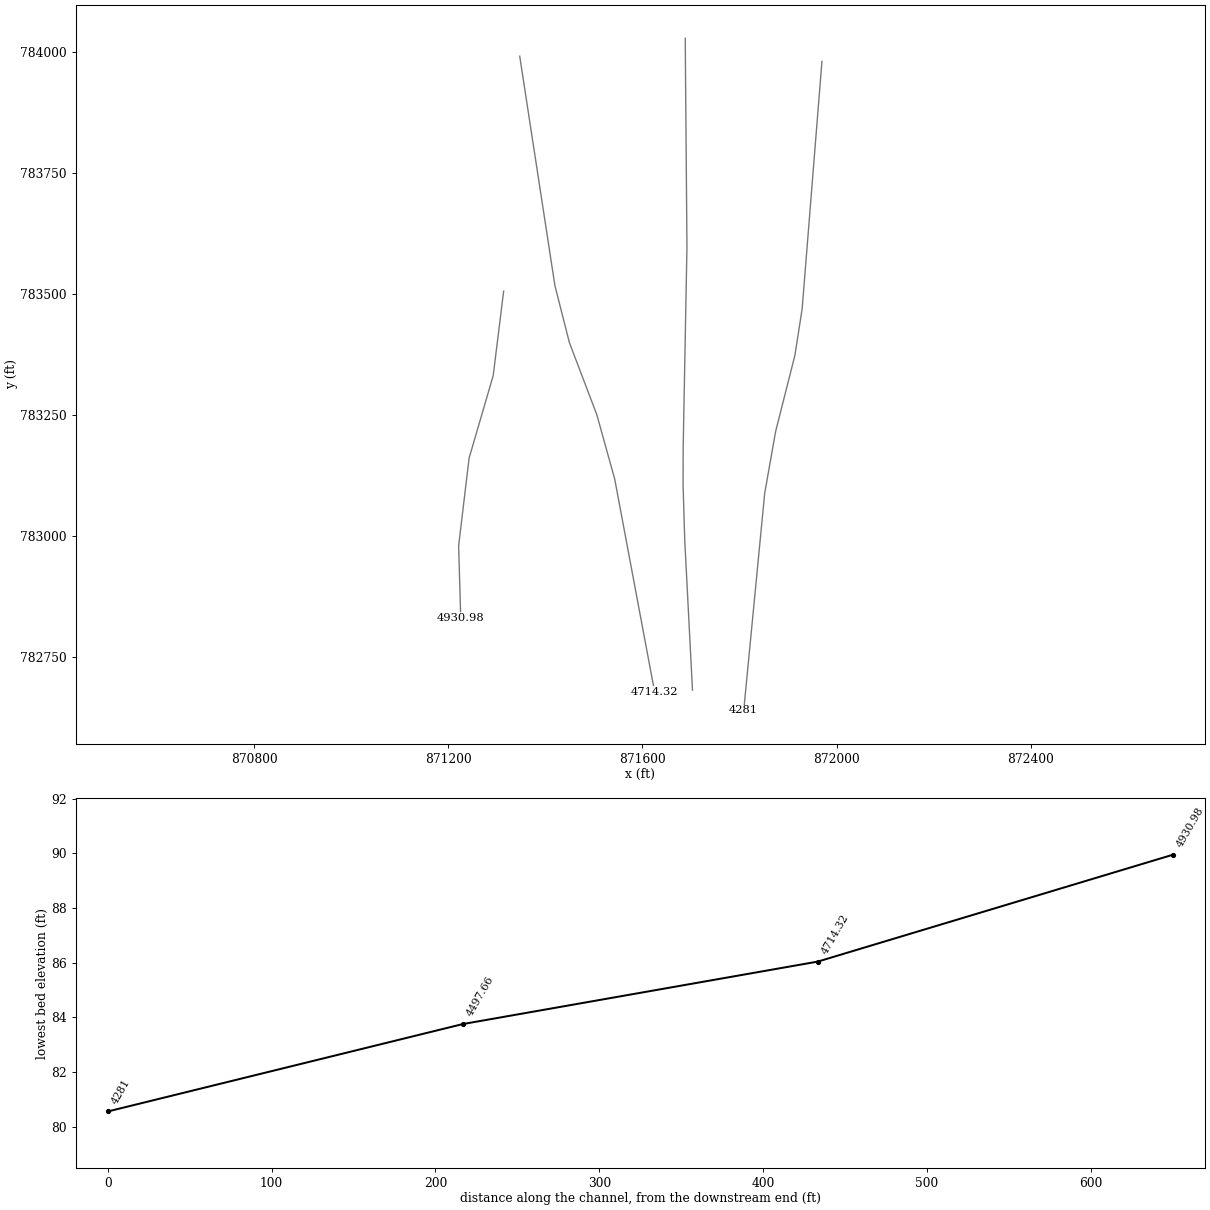
HEC-RAS study 11666_ras.prj: 11666

--- 11666_ras.g01 (geometry) --- (continued)

Type RM Length L Ch R = 3 ,5002.961,,,
BEGIN DESCRIPTION:
END DESCRIPTION:
Bridge Culvert--1,0,-1,-1, 0
Deck Dist Width WeirC Skew NumUp NumDn MinLoCord MaxHiCord MaxSubmerge Is_Ogee
45.296250,40.000000,2.6,0, 41, 40, , , 0.95, 0, 0,0,,
 9787.44 9791.16 9811.61 9821.83 9852.50 9872.94 9893.39 9903.61 9944.50 9952.85
 9958.21 9958.2110027.1510028.2110028.2110055.7510105.9910116.0010136.0210146.03
10156.0410166.0510186.0610196.0710236.0810246.0810256.0810266.0910276.0910296.10
10306.1010316.1010326.1110336.1110346.1110356.1110376.1210386.1210396.1310406.13
10417.72
   99.10   99.19   99.22   99.51   99.98  100.54  101.20  101.64  103.72  104.08
  104.17  104.17  105.34  105.31  105.31  104.76  104.27  104.31  104.24  104.46
  104.42  104.49  105.01  105.19  105.73  105.74  105.87  106.23  106.33  106.75
  107.87  108.40  107.91  107.79  107.57  107.77  108.63  108.55  108.77  108.75
  108.99
 -900.90 -900.81 -900.78 -900.49 -900.02 -899.46 -898.80 -898.36 -896.28 -895.92
 -895.83  100.17  101.34  101.31 -894.69 -895.24 -895.73 -895.69 -895.76 -895.54
 -895.58 -895.51 -894.99 -894.81 -894.27 -894.26 -894.13 -893.77 -893.67 -893.25
 -892.13 -891.60 -892.09 -892.21 -892.43 -892.23 -891.37 -891.45 -891.23 -891.25
 -891.01
 9787.44 9791.16 9811.61 9821.83 9852.50 9872.94 9893.39 9903.61 9944.50 9952.85
 9957.24 9957.2410027.1510027.2410027.2410055.7510095.9810136.0210146.0310156.04
10166.0510186.0610196.0710236.0810246.0810256.0810266.0910276.0910296.1010306.10
10316.1010326.1110336.1110346.1110356.1110376.1210386.1210396.1310406.1310417.72
   99.10   99.19   99.22   99.51   99.98  100.54  101.20  101.64  103.72  104.08
  104.16  104.16  105.34  105.33  105.33  104.76  104.33  104.24  104.46  104.42
  104.49  105.01  105.19  105.73  105.74  105.87  106.23  106.33  106.75  107.87
  108.40  107.91  107.79  107.57  107.77  108.63  108.55  108.77  108.75  108.99
 -900.90 -900.81 -900.78 -900.49 -900.02 -899.46 -898.80 -898.36 -896.28 -895.92
 -895.84  100.16  101.34  101.33 -894.67 -895.24 -895.67 -895.76 -895.54 -895.58
 -895.51 -894.99 -894.81 -894.27 -894.26 -894.13 -893.77 -893.67 -893.25 -892.13
 -891.60 -892.09 -892.21 -892.43 -892.23 -891.37 -891.45 -891.23 -891.25 -891.01
BR Coef=-1 , 0 , 0 ,, 0 ,,,0.8,0,1,0,
WSPro=,,,, 1 ,,,, 0 ,,,, 0 ,,,,-1 ,-1 ,-1 , 0 , 0 , 0 , 0 , 0
BC Design=,, 0 ,, 0 ,,,,,,

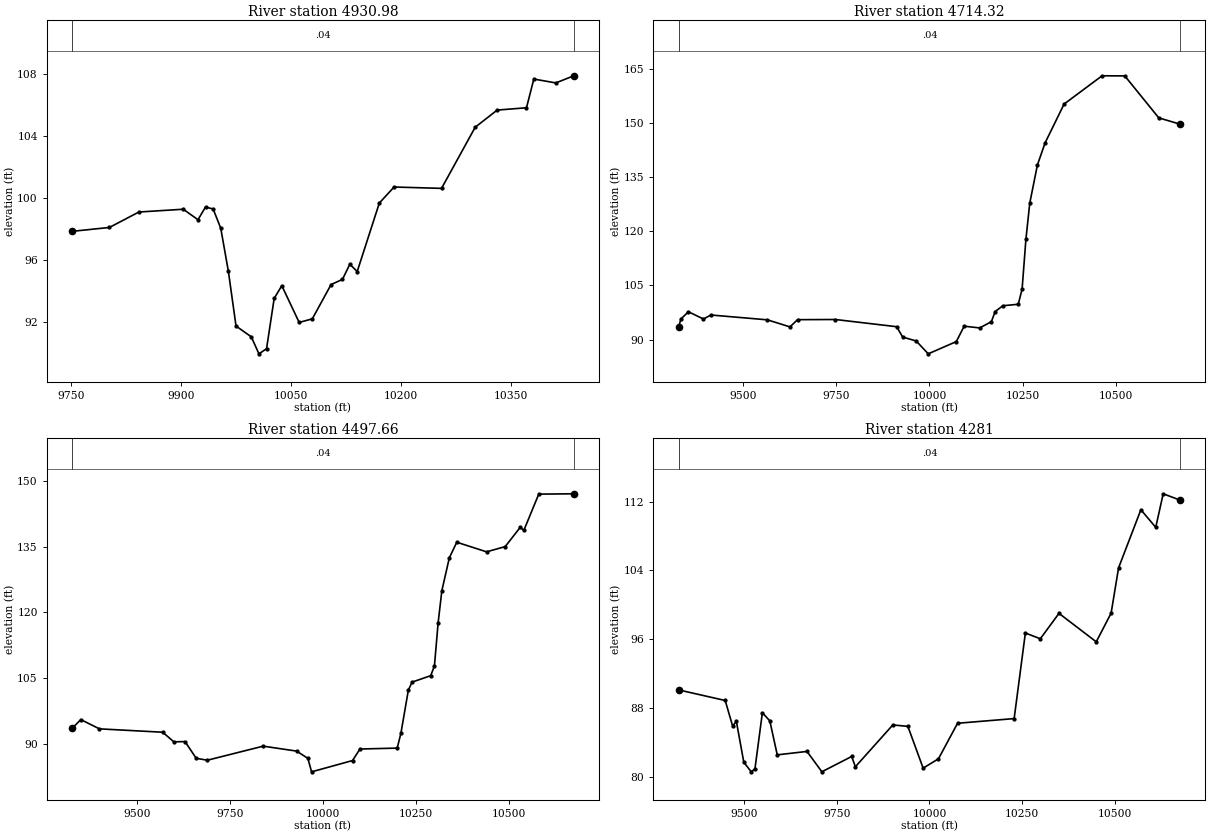
Type RM Length L Ch R = 1 , 4930.98,216.659900,216.659900,216.659900
XS GIS Cut Line= 5
871314.013505846783505.575259522871292.441025406 783330.83816807
871242.824320406783160.415572703871221.251839966782979.206737101
871225.566336095782830.356622159
#Sta/Elev= 30
9750.86197.850119801.82198.101449842.12499.09853 9902.5899.277339922.73298.60177
9933.00699.418179943.42199.294899953.83698.048579964.25195.262269974.66691.73769
9995.49791.0427110005.9189.9434510016.3390.2731910026.7493.5190410037.1694.34321
10060.87   91.9710078.8292.2038910104.4294.4162710119.9594.7485210130.0295.72995
10140.0995.25817 10170.399.6795910190.44100.7122 10255.2100.624310301.12104.5701
10331.14105.677610371.15105.827910381.16107.681410411.17107.431510435.82107.8922
#Mann= 3 , 0 , 0
9750.861    0.04       09750.861    0.04       010435.82    0.04       0
#XS Ineff= 2 , 0
       09938.545        10037.29       0
Bank Sta=9750.861,10435.82
Exp/Cntr=0.3,0.1

Type RM Length L Ch R = 1 , 4714.32,216.659800,216.659800,216.659800
XS GIS Cut Line= 6
871347.082189283783991.274205828871419.598940693783517.094776297
871449.391745415783399.283044135871505.940016095783250.129544378
871542.880985237 783116.73167669871624.915325063782677.711385248
#Sta/Elev= 30
9326.86393.33247 9333.18 95.67699353.31897.693869393.59495.681169413.73296.78912
9565.10695.454079625.88193.497649646.15295.499689747.74695.542969911.95893.54961
9928.28590.679429964.53389.59358 9996.8186.0357210072.0889.4245710093.2193.68917
10134.9593.2116610166.1494.9336510176.4697.7598710197.11 99.356510238.3499.76198
 10248.6103.940810258.85117.746610269.11127.725110289.63138.312710310.15144.4196
10361.28155.203710463.22163.034410524.12162.9994 10615.3 151.38210673.13149.6124
#Mann= 3 , 0 , 0
9326.863    0.04       09326.863    0.04       010673.13    0.04       0
#XS Ineff= 2 , 0
       09893.885        10139.35       0
Bank Sta=9326.863,10673.13
Exp/Cntr=0.3,0.1

Type RM Length L Ch R = 1 , 4497.66,216.659900,216.659900,216.659900
XS GIS Cut Line= 6
871688.092789769784028.524727891 871691.61298723 783596.60285993
871683.889005667783184.194146707871683.631662054 783105.63049462
 871687.08281272782990.656747581871703.013171389782680.799209584
#Sta/Elev= 30
9325.85493.62628 9349.3895.635129399.38193.528349569.38792.761299599.38890.57176
9629.38990.63577 9659.3986.829599689.39186.396059839.40189.593139929.41188.46427
9959.41486.817269969.41583.7503210079.4486.3187210099.4588.9408110199.4889.15069
10209.4892.5445610229.48102.365310239.48104.1607 10289.5105.6288 10299.5107.8347
10309.51117.720710319.51124.985810339.52132.433210359.53135.986310439.63 133.799
 10489.7134.994410529.75139.346110539.76138.689610579.82146.925710674.14147.0076
#Mann= 3 , 0 , 0
9325.854    0.04       09325.854    0.04       010674.14    0.04       0
#XS Ineff= 2 , 0
       09846.063        10144.85       0
Bank Sta=9325.854,10674.14
Exp/Cntr=0.3,0.1

Type RM Length L Ch R = 1 ,    4281,0.000000,0.000000,0.000000
XS GIS Cut Line= 6
871969.724910349783980.538051983871928.922026947 783468.79415203
871914.004405663783372.830333498871874.186472094783215.001569068
871851.738384248783087.220067189871808.610023946782638.910988338
#Sta/Elev= 30
9323.25390.087619449.13288.855039469.186 85.87639479.21386.432099499.26781.67528
9519.32280.553279529.34980.890799549.40387.429899569.457 86.48699589.51282.53008
9669.72982.927419709.88380.559819790.23482.340199800.27881.144789901.20386.00811
9941.82685.846799983.038 80.984110024.3182.06639 10075.9 86.205710228.5386.74938
10258.7796.70953 10299.196.0356210349.4598.9916810449.9795.68055 10490.199.01854
10510.16104.285110570.34111.046610610.47109.001810630.53112.905610676.76 112.155
#Mann= 3 , 0 , 0
9323.253    0.04       09323.253    0.04       010676.76    0.04       0
#XS Ineff= 2 , 0
       09910.595         10108.8       0
Bank Sta=9323.253,10676.76
Exp/Cntr=0.3,0.1